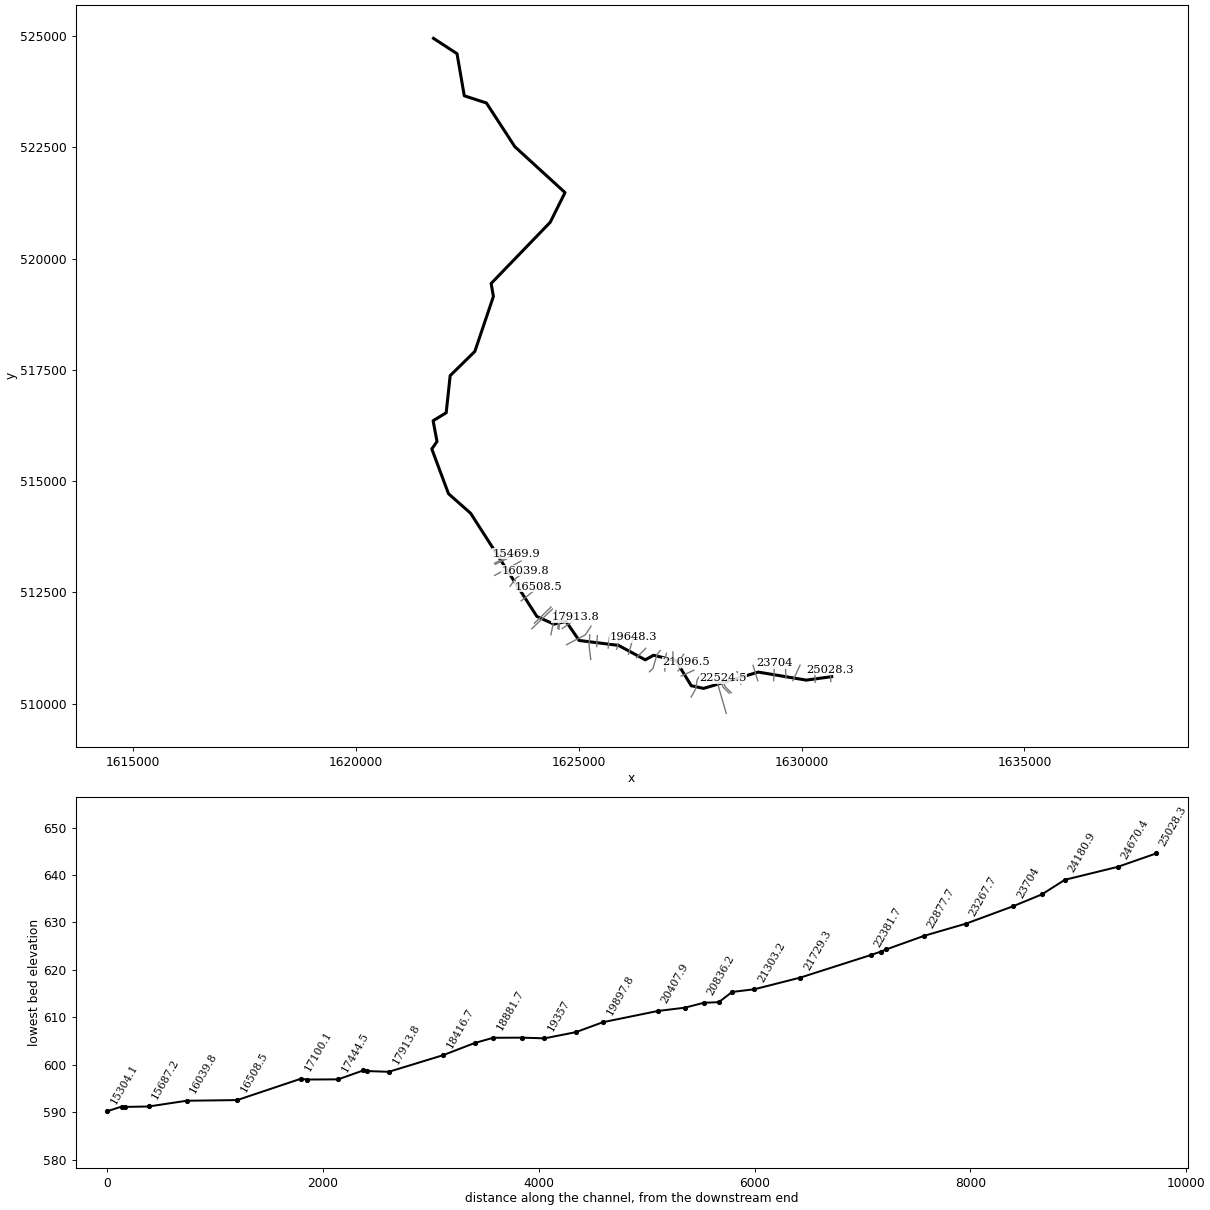
--- FudgesCr.prj (project) ---

Proj Title=FudgesCr
Current Plan=p01
Geom File=g01
Flow File=f01
Plan File=p01
DSS Export Rating Curves=0
DSS Export Rating Curve Sorted=0
DSS Export Volume Flow Curves=0
DXF OffsetX=0
DXF OffsetY=0
DXF ScaleX=0
DXF ScaleY=0

--- FudgesCr.p01 (plan) ---

Plan Title=Floodplain
Program Version=4.00
Geom File=g01
Flow File=f01
K Sum by GR=0
Std Step Tol=0.01
Critical Tol=0.01
Num of Std Step Trials=20
Max Error Tol=0.3
Flow Tol Ratio=0.001
Split Flow NTrial=30
Split Flow Tol=0.02
Split Flow Ratio=0.02
Log Output Level=0
Friction Slope Method=1
Unsteady Friction Slope Method=2
Unsteady Bridges Friction Slope Method=1
Global Log Level=0
CheckData=False
Run HTab=0
Run UNet=0
Run PostProcess=0
UNET Theta=0
UNET Theta Warmup=0
UNET ZTol=0
UNET ZSATol=0
UNET MxIter=0
UNET MaxInSteps=0
UNET DtIC=0
UNET DtMin=0
UNET MaxCRTS=0
UNET WFStab=0
UNET SFStab=0
UNET WFX=0
UNET SFX=0
UNET DSS MLevel=0
UNET DZMax Abort=0
UNET Convert EG Bridges=0
UNET Use Existing IB Tables=0
UNET Froude Limit=0
UNET Froude Power=0
Write IC File=0
Echo Input=False
Echo Output=False
Write Detailed=0

--- FudgesCr.f01 (steady flow) ---

Flow Title=NFF Regression Equation
Program Version=4.10
Number of Profiles= 1
Profile Names=P100yr
River Rch & RM=FudgesCr,Main            ,25028.3
     887
River Rch & RM=FudgesCr,Main            ,24670.4
     890
River Rch & RM=FudgesCr,Main            ,24180.9
     906
River Rch & RM=FudgesCr,Main            ,23267.7
     933
River Rch & RM=FudgesCr,Main            ,22877.7
     944
River Rch & RM=FudgesCr,Main            ,21729.3
     954
River Rch & RM=FudgesCr,Main            ,21303.2
    1082
River Rch & RM=FudgesCr,Main            ,20973
    1089
River Rch & RM=FudgesCr,Main            ,20656.4
    1193
River Rch & RM=FudgesCr,Main            ,19357
    1206
River Rch & RM=FudgesCr,Main            ,18416.7
    1234
River Rch & RM=FudgesCr,Main            ,17913.8
    1338
River Rch & RM=FudgesCr,Main            ,17151
    1346
River Rch & RM=FudgesCr,Main            ,16508.5
    1440
River Rch & RM=FudgesCr,Main            ,16039.8
    1485
River Rch & RM=FudgesCr,Main            ,15469.9
    1509
River Rch & RM=FudgesCr,Main            ,15304.1
    1527
River Rch & RM=FudgesCr,Main            ,13747.9
    1558
River Rch & RM=FudgesCr,Main            ,13171
    1614
River Rch & RM=FudgesCr,Main            ,12458.4
    1619
River Rch & RM=FudgesCr,Main            ,12203.4
    2068
River Rch & RM=FudgesCr,Main            ,10806.5
    2125
River Rch & RM=FudgesCr,Main            ,9755.8
    2136
River Rch & RM=FudgesCr,Main            ,8934.5
    2142
River Rch & RM=FudgesCr,Main            ,7704.4
    2179
River Rch & RM=FudgesCr,Main            ,6965.8
    2187
River Rch & RM=FudgesCr,Main            ,6579.8
    2192
Boundary for River Rch & Prof#=FudgesCr,Main            , 1
Up Type= 0
Dn Type= 3
Dn Slope=0.00123
DSS Import GetInterval= 0
DSS Import GetPeak= 0
DSS Import FillOption= 0

--- FudgesCr.g01 (geometry) ---

Geom Title=USGS 10m DEM
Program Version=4.10

River Reach=FudgesCr        ,Main
Reach XY= 30
     1630676.056      510606.185     1630106.255      510527.755
       1629028.7      510708.204     1627801.642      510341.652
     1627525.234      510401.618     1627183.503      510963.325
     1626680.279      511087.302     1626494.324      510983.365
     1625894.416      511307.867      1625010.59      511418.707
     1624717.319       511846.58     1624444.889      511785.462
     1624063.922      511957.114     1622575.862      514277.757
     1622079.903      514717.147      1621705.88      515721.615
     1621822.558      515889.372      1621735.01      516356.123
     1622028.526      516534.819     1622117.824      517369.896
     1622671.187      517913.142     1623087.675      519149.476
     1623036.638      519440.052     1624362.022      520816.033
     1624693.832       521483.38       1623568.8      522513.457
     1622930.579       523496.15     1622434.428       523657.92
     1622271.614       524603.16     1621744.169      524948.786

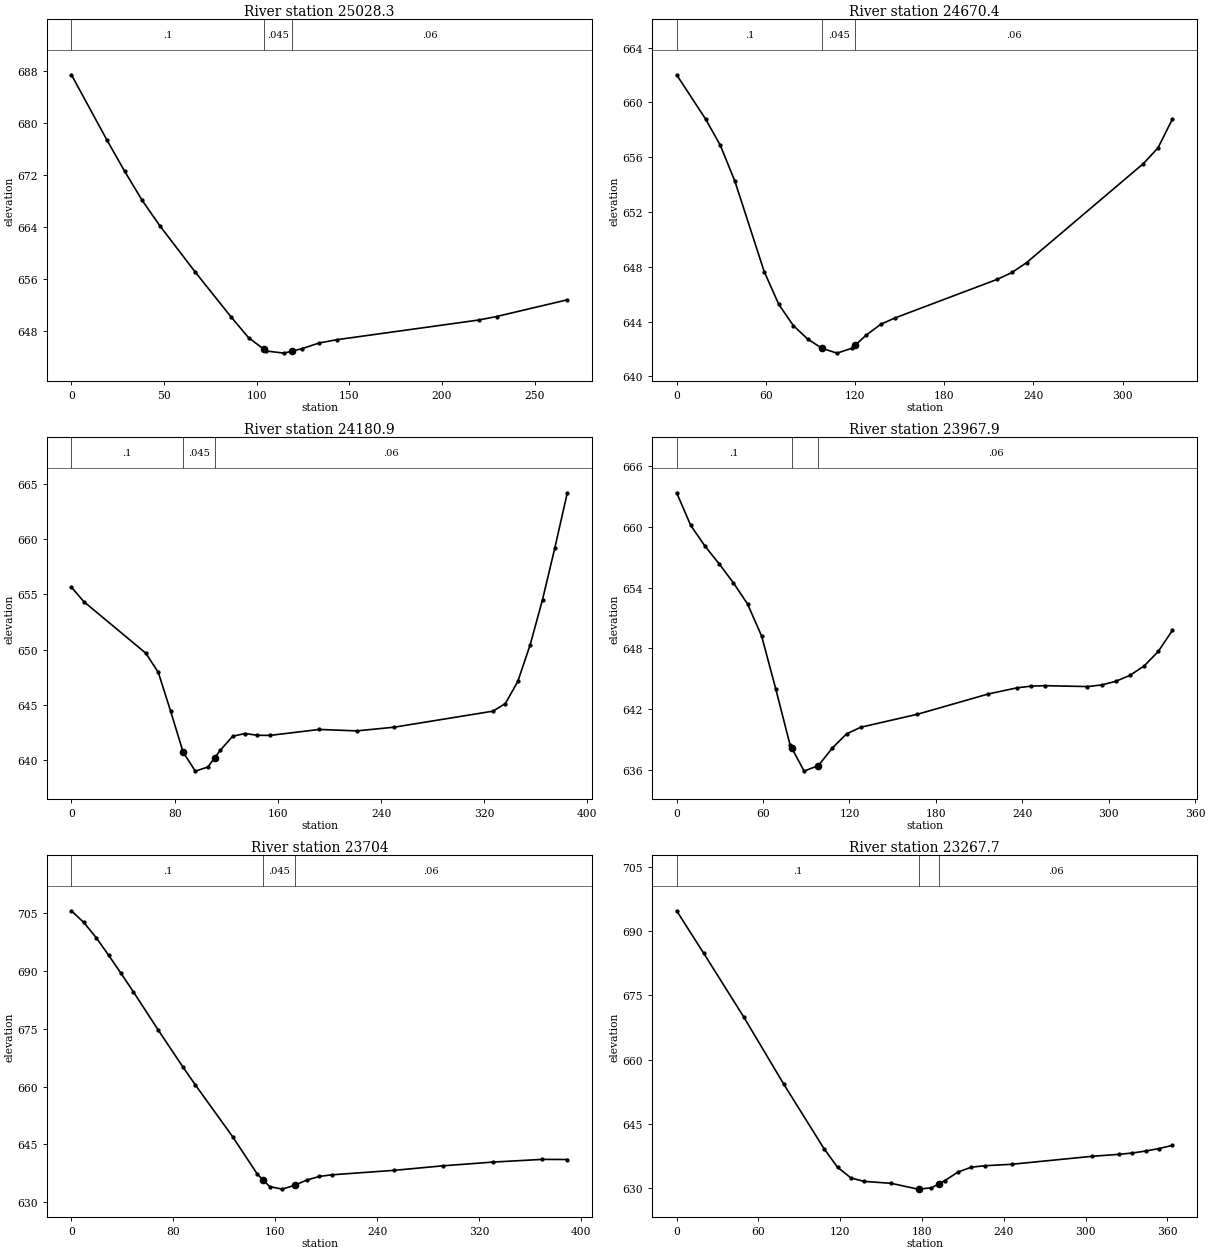
Type RM Length L Ch R = 1 ,25028.3 ,359.6,357.9,355.9
XS GIS Cut Line= 2
     1630655.439      510494.939     1630643.287        510762.3
#Sta/Elev= 18
       0  687.34    19.1  677.33    28.7  672.51    38.2  668.02    47.8  664.09
    66.9  656.97      86  650.16    95.6  646.91   103.9  645.13   105.1  644.87
   114.7  644.54   118.9  644.84   124.3  645.22   133.8  646.11   143.4  646.61
   219.8  649.63   229.4  650.17   267.6  652.74
#Mann= 3 , 0 , 0
       0      .1       0   103.9    .045       0   118.9     .06       0
Bank Sta=103.9,118.9
XS Rating Curve= 0 ,0
Exp/Cntr=0.3,0.1

Type RM Length L Ch R = 1 ,24670.4 ,498.2,489.5,479.4
XS GIS Cut Line= 2
     1630304.088      510479.557     1630291.067       510812.89
#Sta/Elev= 21
       0  662.01    19.6  658.76    29.4  656.86    39.2  654.24    58.9  647.65
    68.7  645.26    78.5  643.71    88.3  642.71    98.1  642.04   107.9   641.7
   117.7  642.05   120.3   642.3   127.6  643.02   137.4  643.81   147.2  644.28
   215.8  647.09   225.7  647.59   235.5  648.31     314  655.53   323.8  656.67
   333.6  658.79
#Mann= 3 , 0 , 0
       0      .1       0    98.1    .045       0   120.3     .06       0
Bank Sta=98.1,120.3
XS Rating Curve= 0 ,0
Exp/Cntr=0.3,0.1

Type RM Length L Ch R = 1 ,24180.9 ,202.3,213,223.6
XS GIS Cut Line= 2
     1629804.745      510515.772     1629965.546      510864.973
#Sta/Elev= 24
       0  655.66     9.6  654.35    57.7  649.67    67.3  647.94    76.9  644.41
    86.5  640.72      96  638.98   105.7  639.35     111  640.18   115.3  640.86
   124.9  642.14   134.6  642.39   144.2  642.23   153.8  642.22   192.2  642.76
   221.1  642.63   249.9  642.96   326.8  644.42   336.4  645.11     346  647.11
   355.6  650.43   365.2  654.54   374.8  659.25   384.4  664.22
#Mann= 3 , 0 , 0
       0      .1       0    86.5    .045       0     111     .06       0
Bank Sta=86.5,111
XS Rating Curve= 0 ,0
Exp/Cntr=0.3,0.1

Type RM Length L Ch R = 1 ,23967.9 ,265.8,263.9,261.8
XS GIS Cut Line= 2
     1629648.495      510573.064     1629634.817      510917.057
#Sta/Elev= 27
       0  663.35     9.8  660.13    19.7  658.09    29.5  656.35    39.3  654.49
    49.2   652.4      59  649.22    68.8  644.02    78.7  638.51    79.9  638.19
    88.5   635.9    98.4  636.45   108.2  638.19     118  639.58   127.9  640.23
   167.2  641.51   216.4  643.51   236.1  644.11   245.9  644.28   255.7  644.33
   285.2  644.24   295.1   644.4   304.9  644.76   314.8  645.35   324.6  646.27
   334.4   647.7   344.3   649.8
#Mann= 3 , 0 , 0
       0      .1       0    79.9    .045       0    98.4     .06       0
Bank Sta=79.9,98.4
XS Rating Curve= 0 ,0
Exp/Cntr=0.3,0.1

Type RM Length L Ch R = 1 ,23704   ,427.4,436.3,444.3
XS GIS Cut Line= 2
     1629374.189      510514.036     1629393.287      510902.925
#Sta/Elev= 23
       0  705.55     9.7  702.53    19.5  698.57    29.2  694.05    38.9  689.36
    48.7  684.53    68.1  674.68    87.6  665.05    97.3  660.44   126.5  647.05
     146  637.31   150.8  635.71   155.7  634.08   165.5  633.43   175.2  634.42
   184.9  635.79   194.7  636.72   204.4  637.14   253.1  638.29     292  639.48
     331  640.44   369.9  641.14   389.4   641.1
#Mann= 3 , 0 , 0
       0      .1       0   150.8    .045       0   175.2     .06       0
Bank Sta=150.8,175.2
XS Rating Curve= 0 ,0
Exp/Cntr=0.3,0.1

Type RM Length L Ch R = 1 ,23267.7 ,389.3,390,388.8
XS GIS Cut Line= 2
     1629018.287        510512.3     1628910.859      510859.765
#Sta/Elev= 24
       0  694.72    19.7  684.89    49.2  669.95    78.6  654.24   108.1   639.2
     118  634.88   127.8  632.37   137.6  631.56   157.3  631.12   176.9  629.76
   177.5  629.78   186.8  630.05   192.5  631.02   196.6  631.72   206.4  633.75
   216.2  634.89   226.1  635.22   245.7  635.56   304.7  637.42   324.4  637.88
   334.2  638.19     344  638.65   353.9  639.23   363.7  639.99
#Mann= 3 , 0 , 0
       0      .1       0   177.5    .045       0   192.5     .06       0
Bank Sta=177.5,192.5
XS Rating Curve= 0 ,0
Exp/Cntr=0.3,0.1

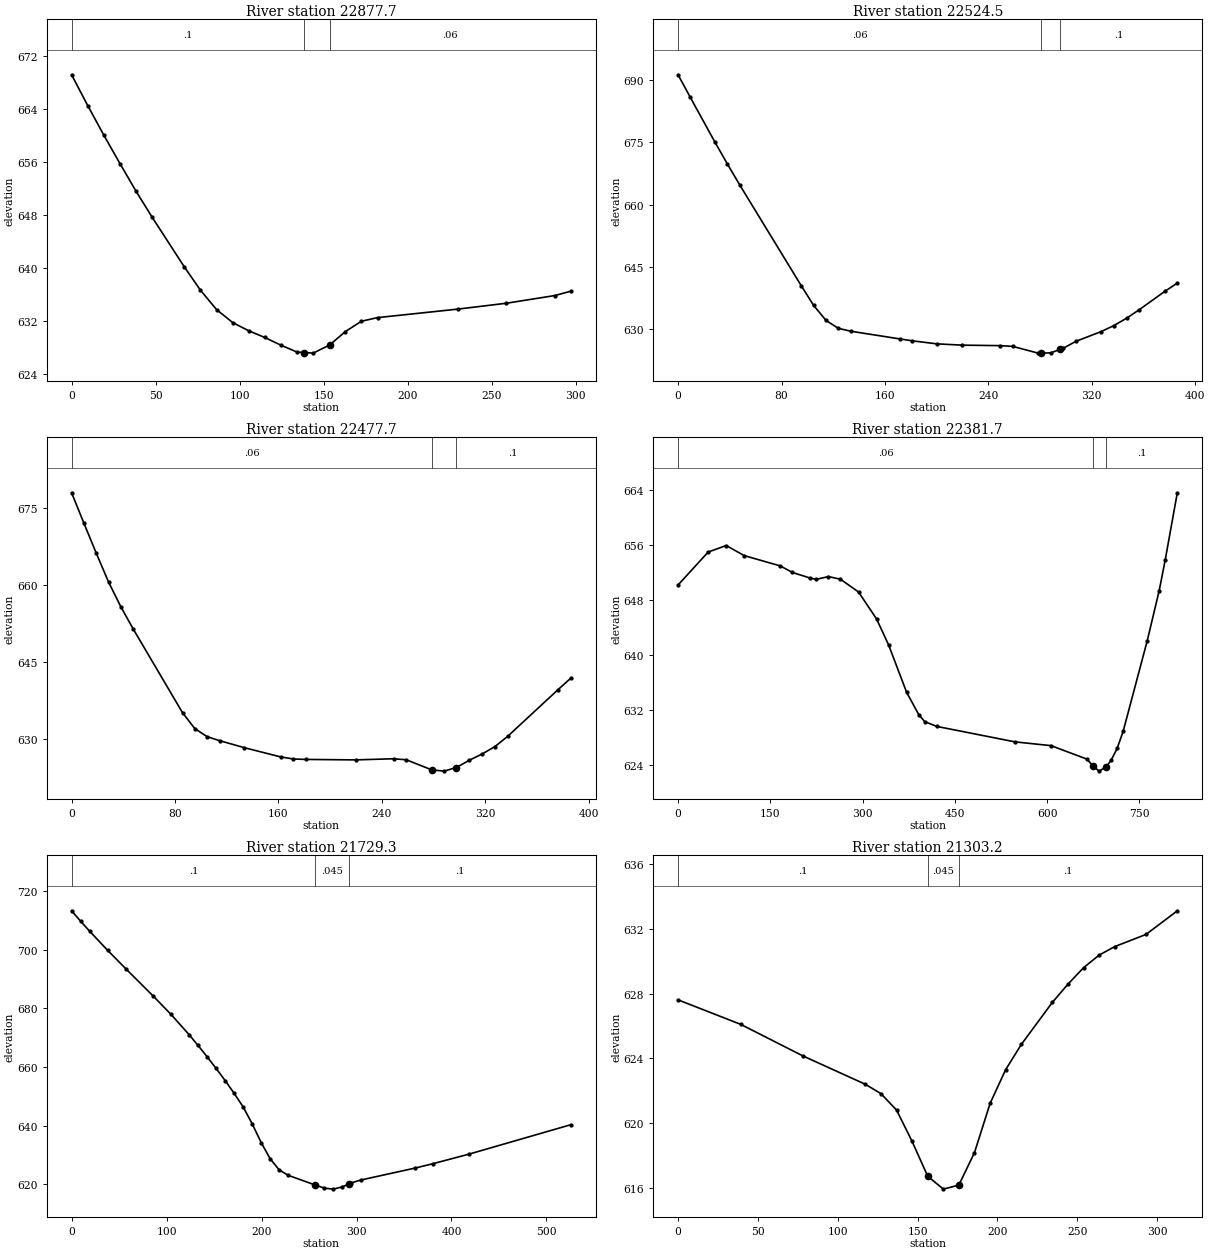
Type RM Length L Ch R = 1 ,22877.7 ,354.4,353.2,352.3
XS GIS Cut Line= 2
     1628638.078      510434.175     1628553.009      510718.897
#Sta/Elev= 24
       0  669.19     9.6  664.54    19.2  660.07    28.8  655.78    38.3  651.64
    47.9  647.71    67.1  640.19    76.7  636.68    86.3  633.75    95.9  631.79
   105.4  630.56     115  629.54   124.6  628.38   134.2  627.34   138.6  627.27
   143.8  627.18   153.6  628.41     163  630.44   172.5  631.99   182.1  632.54
   230.1  633.83   258.8  634.71   287.6  635.87   297.2  636.53
#Mann= 3 , 0 , 0
       0      .1       0   138.6    .045       0   153.6     .06       0
Bank Sta=138.6,153.6
XS Rating Curve= 0 ,0
Exp/Cntr=0.3,0.1

Type RM Length L Ch R = 1 ,22524.5 ,46.8,46.7,46.8
XS GIS Cut Line= 3
     1628422.801      510244.939     1628280.439      510385.564
     1628235.301      510566.119
#Sta/Elev= 28
       0  691.23     9.5  685.78    28.6  674.99    38.1  669.81    47.6  664.79
    95.3   640.5   104.8   635.8   114.4  632.18   123.9  630.27   133.4  629.58
   171.5  627.72     181  627.27   200.1  626.53   219.7  626.22   249.1   626.1
   258.9  625.92   278.5   624.3   280.7  624.31   288.3  624.36   295.7  625.22
   298.1   625.5   307.8  627.14   327.4   629.5   337.2  630.94     347   632.7
   356.8  634.75   376.4  639.13   386.2  641.14
#Mann= 3 , 0 , 0
       0     .06       0   280.7    .045       0   295.7      .1       0
Bank Sta=280.7,295.7
XS Rating Curve= 0 ,0
Exp/Cntr=0.3,0.1

Type RM Length L Ch R = 1 ,22477.7 ,95,96,96.6
XS GIS Cut Line= 3
     1628377.662      510232.786     1628235.301      510373.411
     1628190.162      510553.967
#Sta/Elev= 27
       0  677.85     9.5  671.96    19.1  666.11    28.6  660.53    38.1  655.73
    47.6  651.45    85.8  635.19    95.3  632.11   104.8  630.55   114.4  629.78
   133.4  628.42     162   626.6   171.5  626.22     181  626.13   219.7  626.04
   249.1  626.26   258.9  626.06   278.5  624.11   288.3  623.86   297.1  624.54
   298.1  624.62   307.8  625.99   317.6  627.19   327.4  628.61   337.2  630.58
   376.4  639.69   386.2   641.9
#Mann= 3 , 0 , 0
       0     .06       0   278.5    .045       0   297.1      .1       0
Bank Sta=278.5,297.1
XS Rating Curve= 0 ,0
Exp/Cntr=0.3,0.1

Type RM Length L Ch R = 1 ,22381.7 ,661.3,652.4,609.4
XS GIS Cut Line= 2
     1628309.953      509780.529     1628085.338      510560.286
#Sta/Elev= 30
       0  650.22    48.9  655.01    78.2  655.96   107.5  654.49   166.2  652.99
   185.8  652.04   215.1  651.21   224.9  651.04   244.4  651.44     264  651.05
   293.3   649.2   322.6  645.27   342.2  641.49   371.5  634.59   391.1  631.36
   400.8  630.33   420.4  629.63   547.5  627.38   606.2  626.83   664.8  624.86
   674.6  623.83   684.4  623.12   695.9  623.74   703.9   624.7   713.7  626.43
   723.5  628.92   762.6  642.09   782.1  649.41   791.9  653.89   811.5  663.63
#Mann= 3 , 0 , 0
       0     .06       0   674.6    .045       0   695.9      .1       0
Bank Sta=674.6,695.9
XS Rating Curve= 0 ,0
Exp/Cntr=0.3,0.1

Type RM Length L Ch R = 1 ,21729.3 ,444.8,426.1,403.7
XS GIS Cut Line= 4
     1627521.759       510145.98     1627624.189      510328.272
     1627657.176      510534.869     1627717.939      510623.411
#Sta/Elev= 30
       0   713.2     9.5  709.65      19  706.25      38  699.71      57  693.48
    85.5  684.29   104.6  677.93   123.6  671.04   133.1  667.34   142.6   663.5
   152.1  659.52   161.6  655.38   171.1  651.04   180.6  646.39   190.1  640.65
   199.6  634.24   209.1   628.7   218.6  624.91   228.1  623.07   256.6  619.76
   266.2   618.7   275.7  618.37   285.2  619.16   292.4  620.18   294.7   620.5
   304.2  621.45   361.2  625.51   380.3  627.02   418.3  630.28   525.7  640.32
#Mann= 3 , 0 , 0
       0      .1       0   256.6    .045       0   292.4      .1       0
Bank Sta=256.6,292.4
XS Rating Curve= 0 ,0
Exp/Cntr=0.3,0.1

Type RM Length L Ch R = 1 ,21303.2 ,197.3,206.7,216.3
XS GIS Cut Line= 2
     1627301.273      510619.939     1627585.338       510750.39
#Sta/Elev= 21
       0  627.62    39.1  626.11    78.2  624.15   117.2   622.4     127  621.82
   136.8   620.8   146.5  618.87   156.3  616.71   166.1  615.91   175.8  616.16
   185.6  618.17   195.4  621.22   205.1   623.3   214.9  624.86   234.4  627.47
   244.2   628.6     254  629.62   263.8   630.4   273.5  630.92     293  631.67
   312.6  633.13
#Mann= 3 , 0 , 0
       0      .1       0   156.3    .045       0   175.8      .1       0
Bank Sta=156.3,175.8
XS Rating Curve= 0 ,0
Exp/Cntr=0.3,0.1

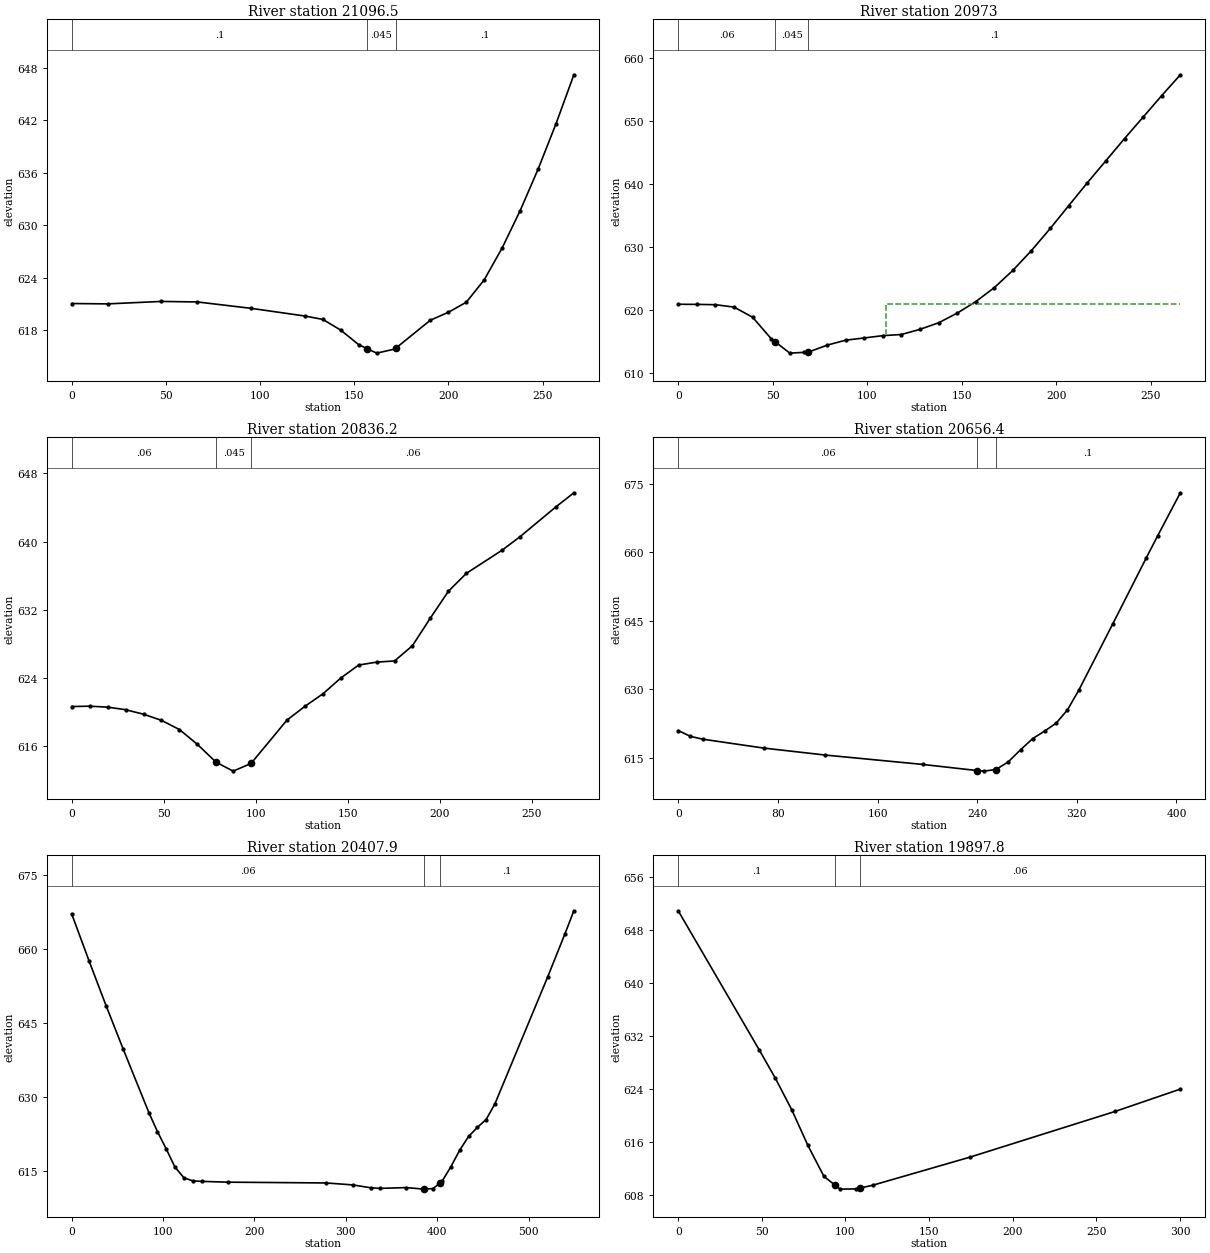
Type RM Length L Ch R = 1 ,21096.5 ,119.2,123.5,127.6
XS GIS Cut Line= 2
     1627230.092      510736.258     1627410.648      510932.439
#Sta/Elev= 22
       0  621.02      19  620.98    47.6  621.26    66.7   621.2    95.2  620.47
   123.8  619.59   133.3   619.2   142.8  617.98   152.4   616.3   156.9  615.85
   161.9  615.34   171.4   615.8   171.9  615.88   190.4  619.11     200  620.02
   209.5  621.17     219  623.73   228.5  627.37   238.1  631.66   247.6   636.4
   257.1  641.59   266.6  647.21
#Mann= 3 , 0 , 0
       0      .1       0   156.9    .045       0   171.9      .1       0
Bank Sta=156.9,171.9
XS Rating Curve= 0 ,0
Exp/Cntr=0.3,0.1

Type RM Length L Ch R = 1 ,20973   ,123.8,136.8,149.9
XS GIS Cut Line= 2
     1627212.731      510882.092     1627353.567      511107.161
#Sta/Elev= 30
       0  620.93     9.8  620.91    19.7  620.86    29.5  620.48    39.3  618.88
    49.2  615.46    51.4  614.95      59  613.19    66.4  613.31    68.8  613.35
    78.7  614.45    88.5  615.24    98.3  615.59   108.2  615.96     118  616.14
   127.8  616.95   137.7     618   147.5  619.52   157.3  621.34   167.2  623.58
     177  626.31   186.8  629.44   196.7  632.93   206.5  636.55   216.3  640.16
   226.2  643.68     236  647.17   245.8  650.56   255.7  653.99   265.5  657.27
#Mann= 3 , 0 , 0
       0     .06       0    51.4    .045       0    68.8      .1       0
#XS Ineff= 2 , 0
                          109.86             621
Permanent Ineff=
       F       F
Bank Sta=51.4,68.8
XS Rating Curve= 0 ,0
Exp/Cntr=0.3,0.1

Type RM Length L Ch R = 1 ,20836.2 ,180.6,179.8,178.7
XS GIS Cut Line= 2
     1627117.245      510889.036     1627113.984      511161.848
#Sta/Elev= 26
       0  620.64     9.7  620.68    19.5  620.57    29.2  620.27      39  619.74
    48.7  619.02    58.5  617.94    68.2  616.21    78.4  614.11    87.7  613.06
    97.4  613.96   116.9  619.04   126.7  620.67   136.4  622.12   146.2  623.99
   155.9  625.51   165.6  625.85   175.4  625.99   185.1  627.78   194.9  631.04
   204.6  634.16   214.4  636.27   233.9     639   243.6  640.58   263.1  644.08
   272.8  645.72
#Mann= 3 , 0 , 0
       0     .06       0    78.4    .045       0    97.4     .06       0
Bank Sta=78.4,97.4
XS Rating Curve= 0 ,0
Exp/Cntr=0.3,0.1

Type RM Length L Ch R = 1 ,20656.4 ,272.3,248.5,236.8
XS GIS Cut Line= 3
     1626932.349      510733.133     1626940.162      511027.404
     1626971.412      511131.571
#Sta/Elev= 20
       0  620.91     9.8  619.64    19.6  619.02    68.7  617.07   117.8  615.55
   196.2  613.49   240.1  612.14   245.3  612.02   255.1  612.37   264.9  614.03
   274.8  616.69   284.6  619.15   294.4  620.84   303.4  622.53   312.5  625.44
   321.6  629.76   348.8  644.25   375.9  658.82     385  663.64   403.1  673.01
#Mann= 3 , 0 , 0
       0     .06       0   240.1    .045       0   255.1      .1       0
Bank Sta=240.1,255.1
XS Rating Curve= 0 ,0
Exp/Cntr=0.3,0.1

Type RM Length L Ch R = 1 ,20407.9 ,514.2,510.1,493
XS GIS Cut Line= 4
     1626588.599      510714.904      1626664.12      510785.217
      1626757.87      511102.925     1626828.182      511194.071
#Sta/Elev= 30
       0  667.07    18.8  657.64    37.5  648.54    56.3   639.7    84.4  626.84
    93.8  622.98   103.2  619.55   112.9  615.81   122.7  613.64   132.4     613
   142.2   612.9   171.4  612.74   278.6  612.58   307.8  612.18   327.3   611.6
     337  611.48   366.2  611.64   385.7  611.33   395.5  611.44   402.7  612.51
   405.2  612.88     415  615.86   424.7  619.24   434.4  622.01     444  623.85
   453.6  625.44   463.2  628.62   520.8  654.26     540  663.13   549.6  667.73
#Mann= 3 , 0 , 0
       0     .06       0   385.7    .045       0   402.7      .1       0
Bank Sta=385.7,402.7
XS Rating Curve= 0 ,0
Exp/Cntr=0.3,0.1

Type RM Length L Ch R = 1 ,19897.8 ,237.9,249.5,260.7
XS GIS Cut Line= 2
     1626294.328      511030.008     1626505.266       511243.55
#Sta/Elev= 14
       0  650.89    48.4  629.95    58.1  625.65    67.8  620.95    77.5  615.56
    87.1  610.88    93.9  609.53    96.8  608.96   106.5  608.99   108.9  609.13
   116.2  609.54   174.3  613.77   261.4  620.68   300.2  624.03
#Mann= 3 , 0 , 0
       0      .1       0    93.9    .045       0   108.9     .06       0
Bank Sta=93.9,108.9
XS Rating Curve= 0 ,0
Exp/Cntr=0.3,0.1

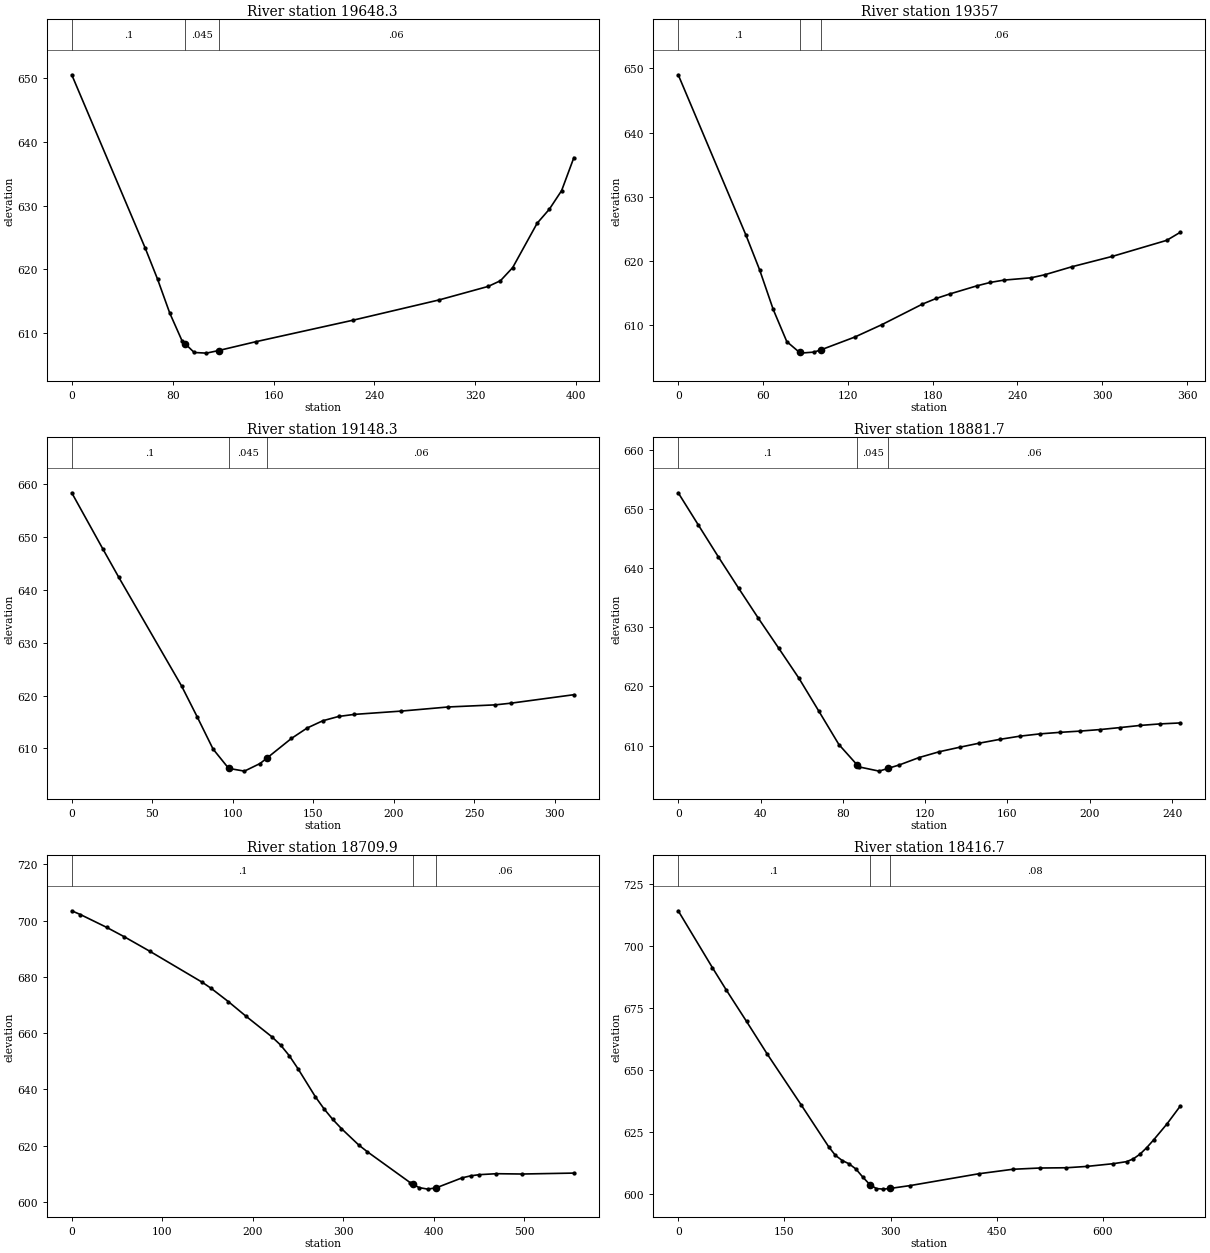
Type RM Length L Ch R = 1 ,19648.3 ,290.8,291.2,291.4
XS GIS Cut Line= 2
     1626117.245      511110.737      1626226.62       511493.55
#Sta/Elev= 19
       0  650.54    58.3  623.32      68  618.49    77.7  613.15    87.4  608.82
      90  608.32    97.1  606.97   106.8  606.87   116.5  607.28   145.7  608.65
   223.3  612.05   291.3  615.22   330.2  617.34   339.9  618.23   349.6  620.29
     369  627.25   378.7  629.46   388.4  632.37   398.1  637.54
#Mann= 3 , 0 , 0
       0      .1       0      90    .045       0   116.5     .06       0
Bank Sta=90,116.5
XS Rating Curve= 0 ,0
Exp/Cntr=0.3,0.1

Type RM Length L Ch R = 1 ,19357   ,205.3,208.8,212
XS GIS Cut Line= 2
      1625851.62      511222.717     1625944.713      511565.494
#Sta/Elev= 23
       0  649.01      48  623.93    57.6  618.55    67.2  612.38    76.8  607.36
    85.8  605.67    86.4  605.56      96  605.72   100.8  606.06   124.8  608.06
     144     610   172.8  613.22   182.4  614.09     192  614.79   211.2  616.06
   220.8   616.6   230.4  616.96   249.6  617.32   259.2  617.79   278.4  619.04
   307.2  620.67   345.6  623.17   355.2  624.43
#Mann= 3 , 0 , 0
       0      .1       0    85.8    .045       0   100.8     .06       0
Bank Sta=85.8,100.8
XS Rating Curve= 0 ,0
Exp/Cntr=0.3,0.1

Type RM Length L Ch R = 1 ,19148.3 ,265.3,266.6,267.8
XS GIS Cut Line= 2
     1625661.516      511248.758     1625697.974      511558.654
#Sta/Elev= 20
       0  658.41    19.5  647.68    29.2  642.42    68.3   621.8      78  615.95
    87.8  609.89    97.5  606.23   107.3  605.71     117  607.15   121.4  608.21
   136.5   611.9   146.3  613.88     156  615.25   165.8  616.06   175.5  616.45
   204.8  617.08     234  617.86   263.3  618.26     273  618.58     312  620.18
#Mann= 3 , 0 , 0
       0      .1       0    97.5    .045       0   121.4     .06       0
Bank Sta=97.5,121.4
XS Rating Curve= 0 ,0
Exp/Cntr=0.3,0.1

Type RM Length L Ch R = 1 ,18881.7 ,171.8,171.8,171.7
XS GIS Cut Line= 2
     1625404.033      511283.855     1625419.328      511527.404
#Sta/Elev= 28
       0  652.69     9.8  647.24    19.5  641.87    29.3   636.6      39  631.47
    48.8  626.46    58.6   621.4    68.3  615.83    78.1  610.16      87  606.71
    87.8   606.4    97.6  605.68     102  606.15   107.4  606.72   117.1  607.98
   126.9  608.96   136.7  609.71   146.4  610.41   156.2  611.04   165.9  611.58
   175.7  611.97   185.5  612.23   195.2  612.44     205   612.7   214.8  613.04
   224.5   613.4   234.3  613.66     244  613.82
#Mann= 3 , 0 , 0
       0      .1       0      87    .045       0     102     .06       0
Bank Sta=87,102
XS Rating Curve= 0 ,0
Exp/Cntr=0.3,0.1

Type RM Length L Ch R = 1 ,18709.9 ,315.6,293.2,270.5
XS GIS Cut Line= 3
     1625270.234      510992.578     1625233.775      511307.682
       1625249.4      511544.661
#Sta/Elev= 30
       0  703.48     9.6  702.15    38.4  697.63    57.7  694.32    86.5  689.06
   144.2  678.08   153.8  675.98     173  671.22   192.2   666.1   221.1  658.71
   230.7  655.79   240.3     652   249.9  647.39   269.1  637.42   278.8  633.07
   288.4  629.33     298  626.07   317.2  620.22   326.7  617.83   374.2  606.82
   377.5  606.23   383.7  605.13   393.2  604.58   402.7  605.05   431.2  608.59
   440.7   609.3   450.2  609.72   469.2  610.06   497.7  609.95   554.7  610.28
#Mann= 3 , 0 , 0
       0      .1       0   377.5    .045       0   402.7     .06       0
Bank Sta=377.5,402.7
XS Rating Curve= 0 ,0
Exp/Cntr=0.3,0.1

Type RM Length L Ch R = 1 ,18416.7 ,494.7,502.9,505.4
XS GIS Cut Line= 3
     1624729.224      511324.279     1625147.801      511544.071
     1625278.703      511740.946
#Sta/Elev= 30
       0   714.1    48.2  691.25    67.5  682.38    96.5  669.55   125.4  656.55
   173.7  635.92   212.3  619.17   221.9  615.64   231.6  613.54   241.2  612.22
   250.9  610.13   260.5  606.93   270.7  603.81   279.8  602.25   289.4  602.01
   299.1  602.28     328  603.46   424.5   608.2   472.8  610.01   510.6  610.51
   548.4  610.62   576.8  611.15   614.6  612.26   633.5  613.09     643  614.23
   652.4  616.13   661.9  618.76   671.4   621.8   690.3  628.25   709.2  635.49
#Mann= 3 , 0 , 0
       0      .1       0   270.7    .045       0   299.1     .08       0
Bank Sta=270.7,299.1
XS Rating Curve= 0 ,0
Exp/Cntr=0.3,0.1

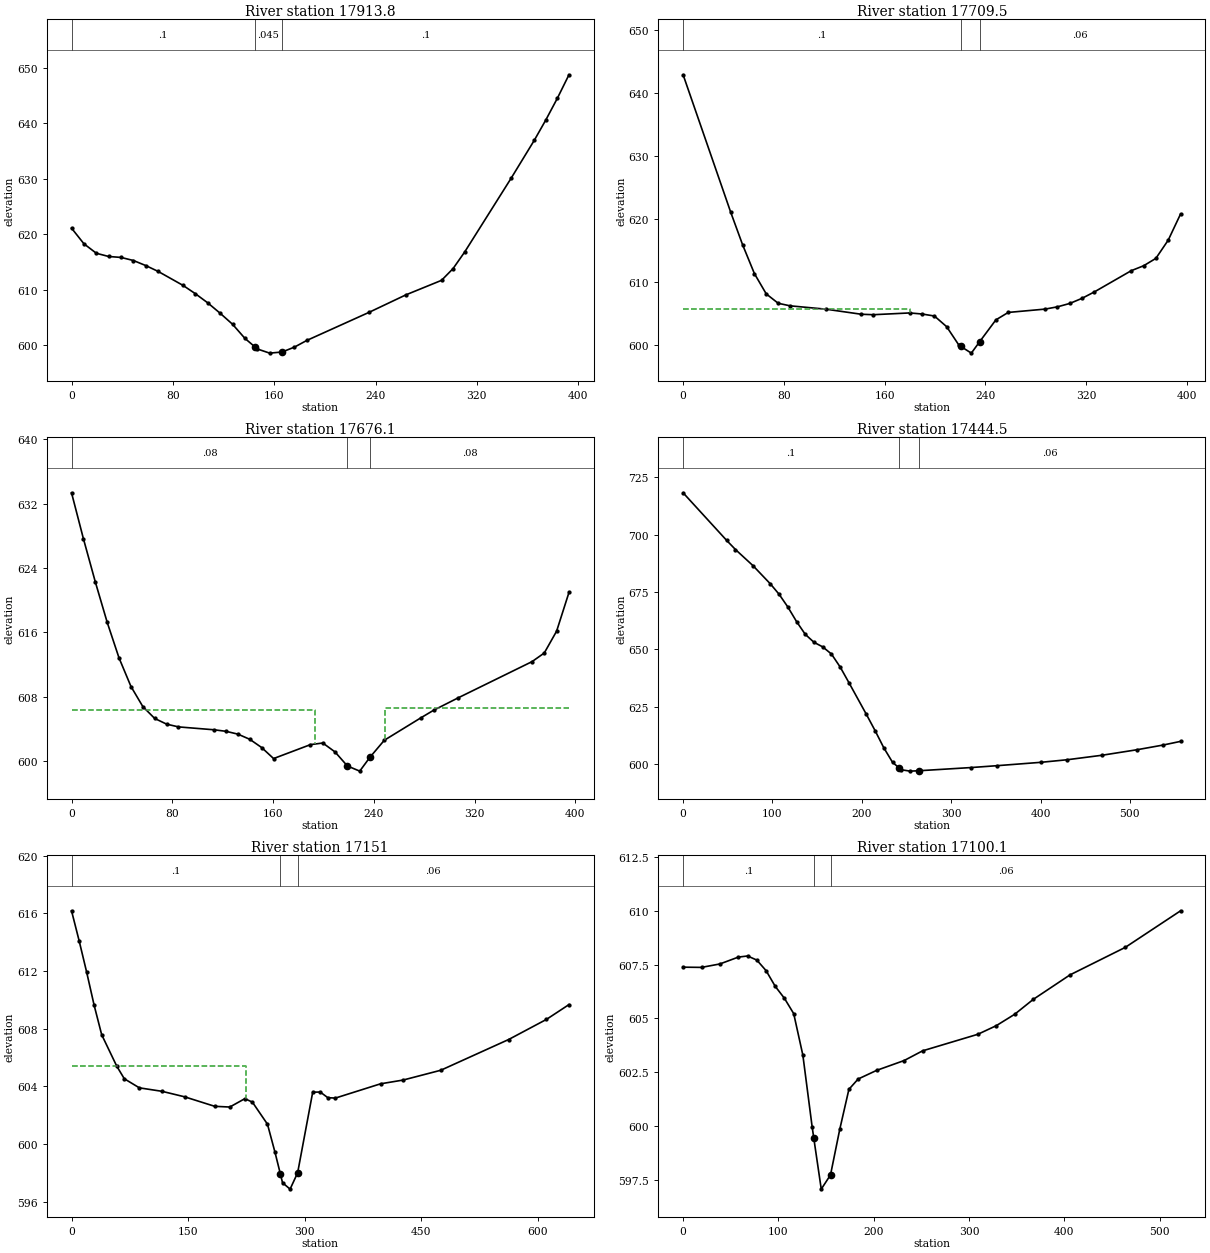
Type RM Length L Ch R = 1 ,17913.8 ,199.6,204.3,206.8
XS GIS Cut Line= 3
     1624631.307        511687.3     1624856.134       511843.55
     1624928.182      511938.168
#Sta/Elev= 30
       0  621.09     9.8  618.26    19.6  616.55    29.3  615.97    39.1   615.8
    48.9  615.24    58.7  614.32    68.4  613.27      88  610.75    97.8  609.24
   107.6  607.58   117.3  605.72   127.1  603.73   136.9  601.17   144.6  599.67
   146.7  599.26   156.4  598.51   166.2  598.71     176   599.6   185.8  600.81
   234.7  605.86     264  609.04   292.1  611.66   301.2  613.78   310.4  616.79
     347  630.09   365.3  636.95   374.4  640.62   383.6  644.58   392.7  648.79
#Mann= 3 , 0 , 0
       0      .1       0   144.6    .045       0   166.2      .1       0
Bank Sta=144.6,166.2
XS Rating Curve= 0 ,0
Exp/Cntr=0.3,0.1

Type RM Length L Ch R = 1 ,17709.5 ,34.5,33.3,33.2
XS GIS Cut Line= 3
     1624557.523      511669.071      1624572.28      511828.793
     1624738.078      511994.592
#Sta/Elev= 30
       0  642.85    37.7  621.08    47.2  615.88    56.6  611.29      66  608.07
    75.5  606.58    84.9  606.18   113.2  605.65   141.5  604.84     151  604.77
   179.9  605.05   189.7  604.88   199.5  604.56   209.2  602.87     219  599.92
   220.4  599.74   228.8  598.67   235.4  600.48   248.3  603.95   258.1  605.13
   287.4  605.66   297.2  606.02     307  606.56   316.7  607.37   326.5  608.39
   355.8  611.76   365.6  612.54   375.3  613.71   385.1   616.6   394.9  620.75
#Mann= 3 , 0 , 0
       0      .1       0   220.4    .045       0   235.4     .06       0
#XS Ineff= 2 , 0
          179.72  605.66
Permanent Ineff=
       F       F
Bank Sta=220.4,235.4
XS Rating Curve= 0 ,0
Exp/Cntr=0.3,0.1

Type RM Length L Ch R = 1 ,17676.1 ,216.7,231.6,244.8
XS GIS Cut Line= 3
     1624532.349      511690.772     1624547.106      511850.494
     1624712.905      512016.293
#Sta/Elev= 30
       0  633.33     9.4  627.65    18.9  622.26    28.3  617.26    37.7  612.84
    47.2  609.29    56.6   606.8      66  605.33    75.5  604.62    84.9  604.28
   113.2  603.92   122.7  603.73   132.1  603.38   141.5  602.74     151  601.71
   160.4  600.35   189.7  602.08   199.5  602.28   209.2  601.17     219  599.43
   228.8  598.79   236.9  600.51   248.3  602.62   277.6  605.43   287.4  606.34
     307  607.89   365.6  612.38   375.3  613.45   385.1  616.16   394.9  620.96
#Mann= 3 , 0 , 0
       0     .08       0     219    .045       0   236.9     .08       0
#XS Ineff= 2 , 0
          193.24  606.42  249.01          606.58
Permanent Ineff=
       F       F
Bank Sta=219,236.9
XS Rating Curve= 0 ,0
Exp/Cntr=0.3,0.1

Type RM Length L Ch R = 1 ,17444.5 ,307.5,293.5,278.7
XS GIS Cut Line= 2
     1624376.533      511546.241     1624491.551      512090.946
#Sta/Elev= 30
       0  718.25    48.8  697.47    58.6  693.52    78.1  686.53    97.7  678.53
   107.4  674.03   117.2  668.47     127  662.09   136.7  656.55   146.5  653.07
   156.3  651.07     166  647.97   175.8  642.28   185.6  635.46   205.1  621.66
   214.9  614.53   224.6  607.08   234.4  600.75   241.7  598.34   244.2  597.52
   253.9  596.92   263.7  597.08   322.3  598.48   351.6   599.3   400.4  600.76
   429.8  601.88   468.8  603.84   507.9  606.24   537.2  608.29   556.7  609.89
#Mann= 3 , 0 , 0
       0      .1       0   241.7    .045       0   263.7     .06       0
Bank Sta=241.7,263.7
XS Rating Curve= 0 ,0
Exp/Cntr=0.3,0.1

Type RM Length L Ch R = 1 ,17151   ,50,50.9,51.9
XS GIS Cut Line= 2
     1623947.317      511682.682     1624411.255      512123.498
#Sta/Elev= 30
       0  616.17     9.7  614.11    19.4  611.93    29.1  609.62    38.8  607.58
    58.2   605.4    67.9  604.53    87.3   603.9   116.4  603.66   145.4  603.28
   184.2  602.62   203.6  602.57     223  603.15   232.7  602.91   252.1  601.38
   261.8  599.43   268.7  597.93   271.5  597.32   281.2  596.88   290.9  598.01
   310.3   603.6     320  603.61   329.7  603.22   339.4  603.19   397.6  604.18
   426.6  604.44   475.1  605.12   562.4  607.25   610.9  608.64     640  609.67
#Mann= 3 , 0 , 0
       0      .1       0   268.7    .045       0   290.9     .06       0
#XS Ineff= 2 , 0
          224.79  605.42
Permanent Ineff=
       F       F
Bank Sta=268.7,290.9
XS Rating Curve= 0 ,0
Exp/Cntr=0.3,0.1

Type RM Length L Ch R = 1 ,17100.1 ,592.5,591.6,589.1
XS GIS Cut Line= 2
      1624007.61      511806.658     1624380.873      512171.241
#Sta/Elev= 28
       0  607.38    19.3  607.37    38.6  607.53      58  607.85    67.6   607.9
    77.3  607.71      87  607.22    96.6  606.49   106.3  605.93     116  605.22
   125.6  603.29   135.3  599.97   137.1  599.42   144.9  597.06   154.6  597.72
   164.3  599.84   173.9   601.7   183.6  602.18   202.9  602.58   231.9  603.04
   251.2  603.49   309.2  604.26   328.5  604.66   347.8  605.19   367.2  605.88
   405.8  607.02   463.8   608.3   521.8     610
#Mann= 3 , 0 , 0
       0      .1       0   137.1    .045       0   154.6     .06       0
Bank Sta=137.1,154.6
XS Rating Curve= 0 ,0
Exp/Cntr=0.3,0.1

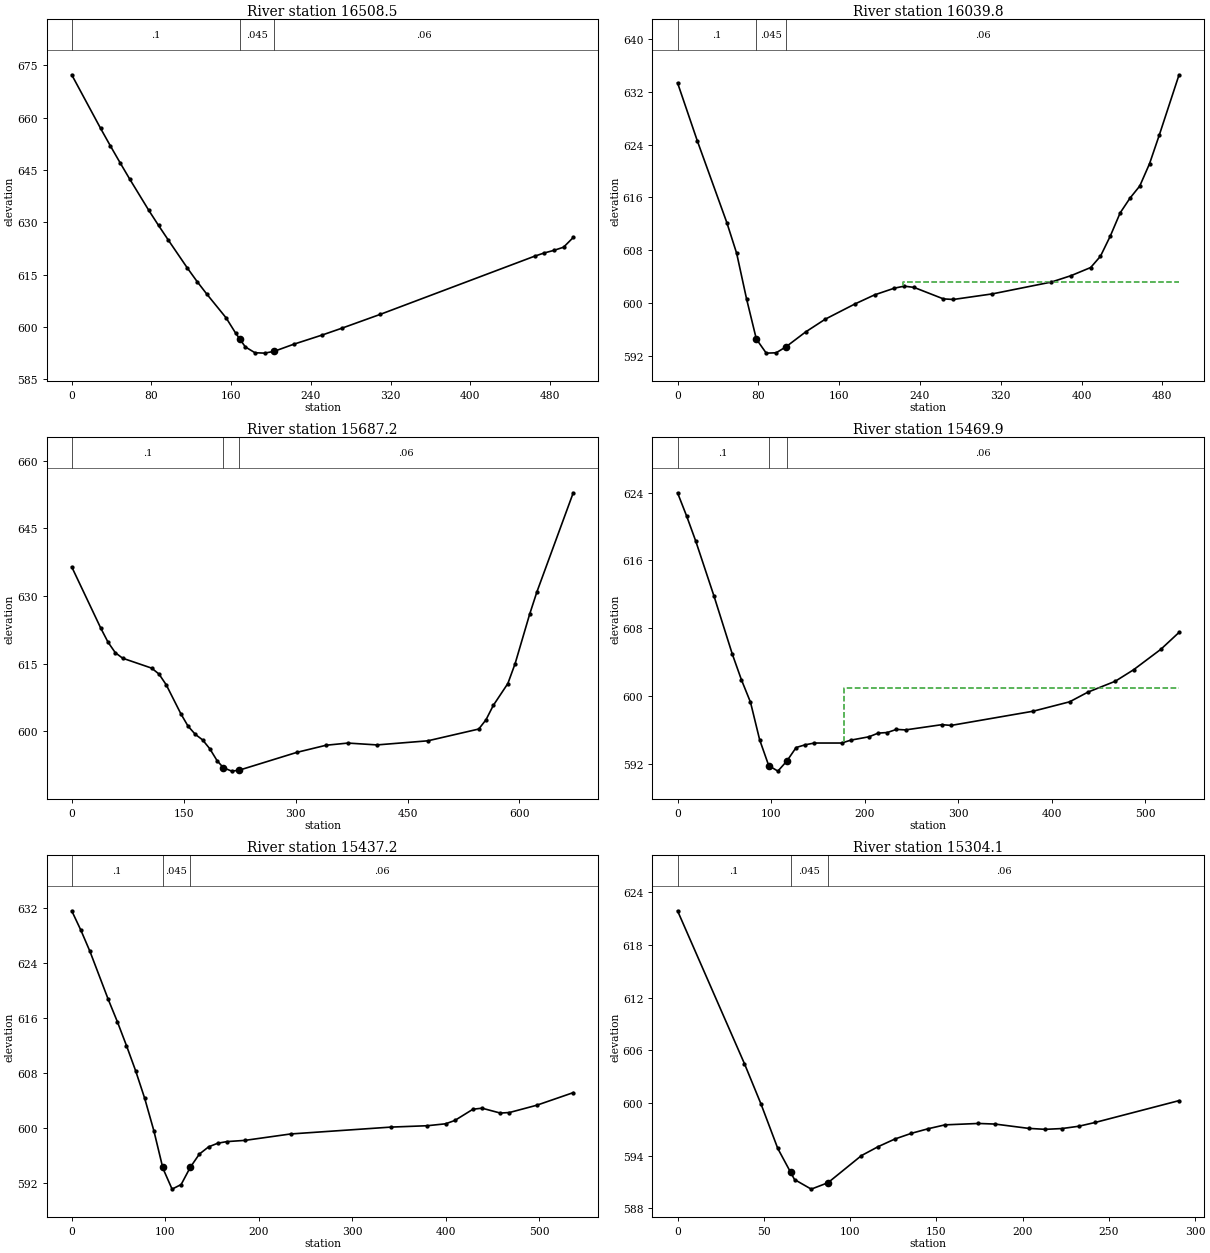
Type RM Length L Ch R = 1 ,16508.5 ,462.4,468.7,474.5
XS GIS Cut Line= 2
     1623710.301       512307.96     1624103.096       512622.63
#Sta/Elev= 27
       0  672.26      29   656.9    38.7  651.95    48.4  647.14    58.1  642.44
    77.4  633.41    87.1  629.13    96.8  624.98   116.1   616.9   125.8  613.06
   135.5  609.48   154.9  602.66   164.5  598.28   168.6  596.61   174.2  594.33
   183.9  592.66   193.6  592.55   203.2  593.07   222.6  595.08   251.6  597.76
     271  599.68   309.7  603.66   464.6  620.32   474.3  621.25   483.9  621.98
   493.6  622.89   503.3  625.67
#Mann= 3 , 0 , 0
       0      .1       0   168.6    .045       0   203.2     .06       0
Bank Sta=168.6,203.2
XS Rating Curve= 0 ,0
Exp/Cntr=0.3,0.1

Type RM Length L Ch R = 1 ,16039.8 ,362.6,352.6,341.6
XS GIS Cut Line= 3
     1623460.338      512635.807     1623585.338      512810.286
     1623806.692      512984.765
#Sta/Elev= 30
       0  633.36    19.5   624.6    48.8  612.18    58.5  607.54    68.3  600.64
      78  594.54    87.8  592.41    97.6  592.46   107.3  593.36   126.8  595.62
   146.3  597.56   175.6  599.86   195.1  601.24   214.6  602.25   224.4  602.56
   234.1  602.37   263.2  600.63     273  600.54   311.8  601.39   370.1  603.18
   389.6  604.15     409  605.38   418.7  607.09   428.4  610.14   438.2  613.66
   447.9  615.89   457.6  617.73   467.3  621.12     477  625.48   496.5  634.58
#Mann= 3 , 0 , 0
       0      .1       0      78    .045       0   107.3     .06       0
#XS Ineff= 2 , 0
                          223.24          603.25
Permanent Ineff=
       F       F
Bank Sta=78,107.3
XS Rating Curve= 0 ,0
Exp/Cntr=0.3,0.1

Type RM Length L Ch R = 1 ,15687.2 ,218.3,217.3,216.1
XS GIS Cut Line= 2
     1623115.682      512880.876      1623705.96      513202.057
#Sta/Elev= 30
       0  636.47      39  622.86    48.7  619.76    58.4  617.45    68.2  616.23
   107.1  614.03   116.9  612.72   126.6  610.34   146.1  603.95   155.8  601.18
   165.6  599.35   175.3  598.13     185  596.16   194.8  593.51   203.2  591.96
   214.3   591.2     224  591.39   301.9  595.37   340.9  596.94   370.1  597.42
     409  597.01   477.2  597.92   545.4  600.53   555.1  602.58   564.9  605.77
   584.4  610.62   594.1  615.01   613.6  625.98   623.3  630.92     672  652.89
#Mann= 3 , 0 , 0
       0      .1       0   203.2    .045       0     224     .06       0
Bank Sta=203.2,224
XS Rating Curve= 0 ,0
Exp/Cntr=0.3,0.1

Type RM Length L Ch R = 1 ,15469.9 ,32.8,32.8,32.7
XS GIS Cut Line= 2
     1623128.993      513127.838     1623610.764      513363.515
#Sta/Elev= 30
       0  623.99     9.8  621.22    19.5  618.27      39  611.78    58.5  604.95
    68.3   601.9      78  599.25    87.8  594.81    97.5  591.76   107.3  591.11
     117  592.32   126.8   593.9   136.5  594.22   146.3  594.43   175.5  594.43
   185.3  594.77   204.8  595.17   214.5   595.6   224.3  595.67     234  596.04
   243.8  595.98   282.8   596.6   292.5  596.51   380.3  598.19   419.3   599.3
   438.8  600.44   468.1  601.73   487.6  603.08   516.8   605.5   536.3   607.5
#Mann= 3 , 0 , 0
       0      .1       0    97.5    .045       0     117     .06       0
#XS Ineff= 2 , 0
                          178.31           600.9
Permanent Ineff=
       F       F
Bank Sta=97.5,117
XS Rating Curve= 0 ,0
Exp/Cntr=0.3,0.1

Type RM Length L Ch R = 1 ,15437.2 ,134.5,133.1,131.8
XS GIS Cut Line= 2
     1623112.066      513155.182     1623593.836      513390.859
#Sta/Elev= 30
       0  631.65     9.8  628.82    19.5  625.74      39  618.78    48.8  615.52
    58.5  612.06    68.3   608.4      78  604.39    87.8  599.68    97.2  594.38
    97.5  594.21   107.3  591.18     117  591.85   126.8  594.36   136.5  596.28
   146.3  597.32     156  597.85   165.8  598.09   185.3  598.27     234   599.2
   341.3   600.2   380.3   600.4   399.8  600.68   409.6  601.16   429.1   602.8
   438.8  602.95   458.3  602.24   468.1  602.32   497.3  603.38   536.3  605.21
#Mann= 3 , 0 , 0
       0      .1       0    97.2    .045       0   126.8     .06       0
Bank Sta=97.2,126.8
XS Rating Curve= 0 ,0
Exp/Cntr=0.3,0.1

Type RM Length L Ch R = 1 ,15304.1 ,231.3,236.2,240.1
XS GIS Cut Line= 2
     1623085.338      513294.661     1623353.567       513406.64
#Sta/Elev= 22
       0   621.9    38.8  604.48    48.4  599.88    58.1  594.83    65.5  592.13
    67.8  591.29    77.5   590.2    87.2  590.93   106.6  594.02   116.3  595.04
     126  595.91   135.6  596.56   145.3  597.08     155  597.52   174.4  597.68
   184.1  597.61   203.5  597.12   213.2  597.01   222.8   597.1   232.5  597.36
   242.2   597.8   290.7  600.28
#Mann= 3 , 0 , 0
       0      .1       0    65.5    .045       0    87.2     .06       0
Bank Sta=65.5,87.2
XS Rating Curve= 0 ,0
Exp/Cntr=0.3,0.1