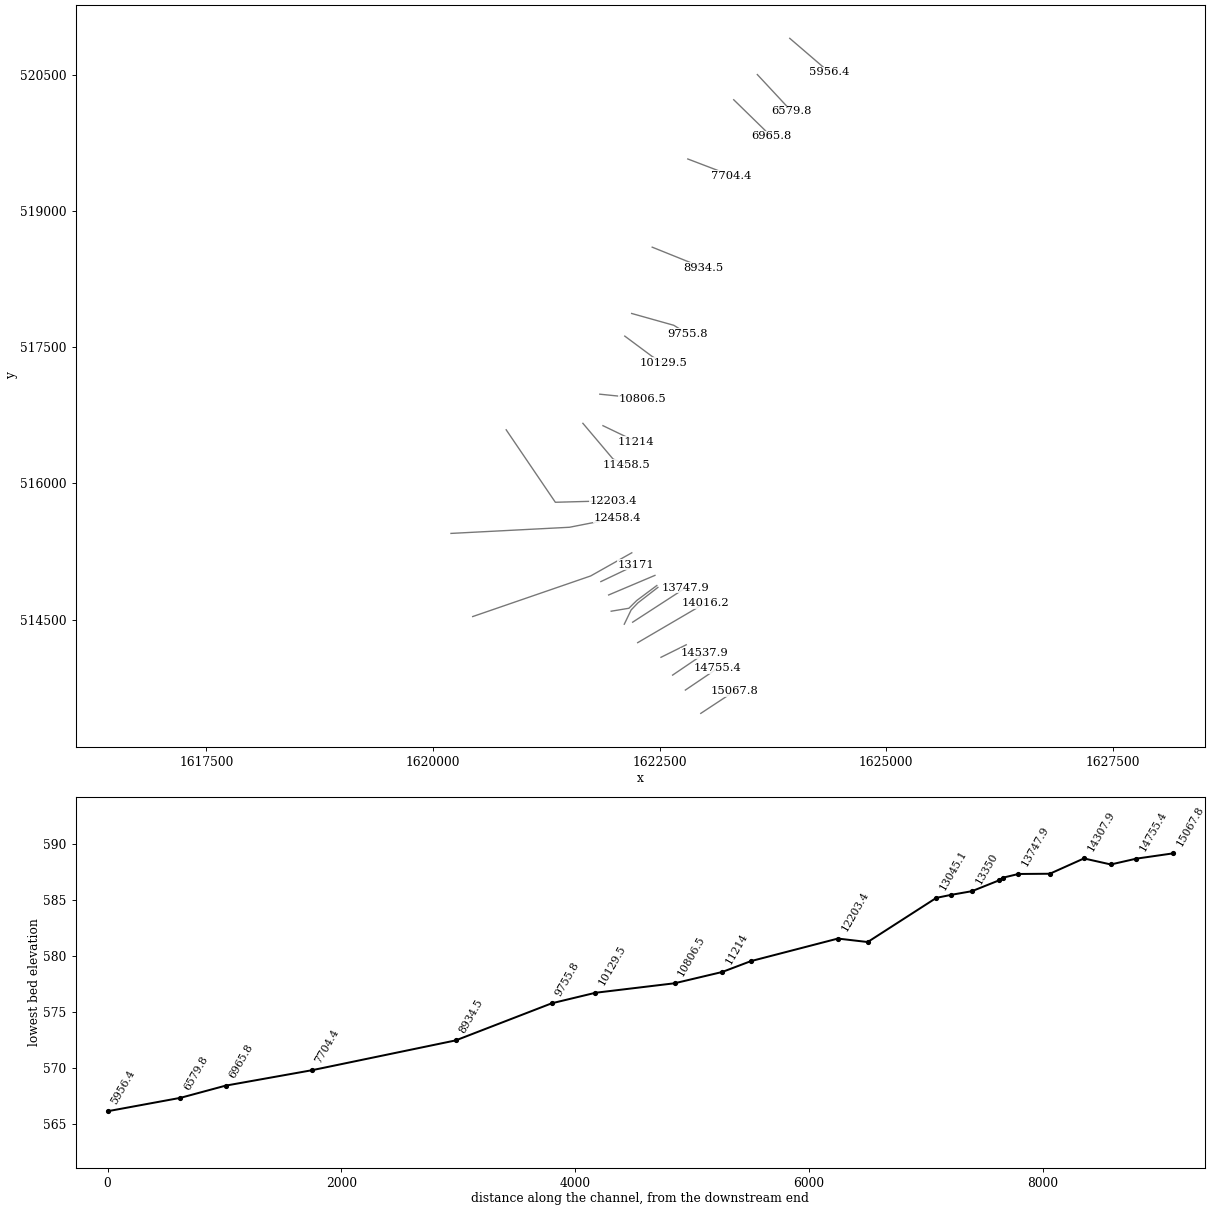
HEC-RAS study FudgesCr.prj: FudgesCr

--- FudgesCr.g01 (geometry) --- (continued)

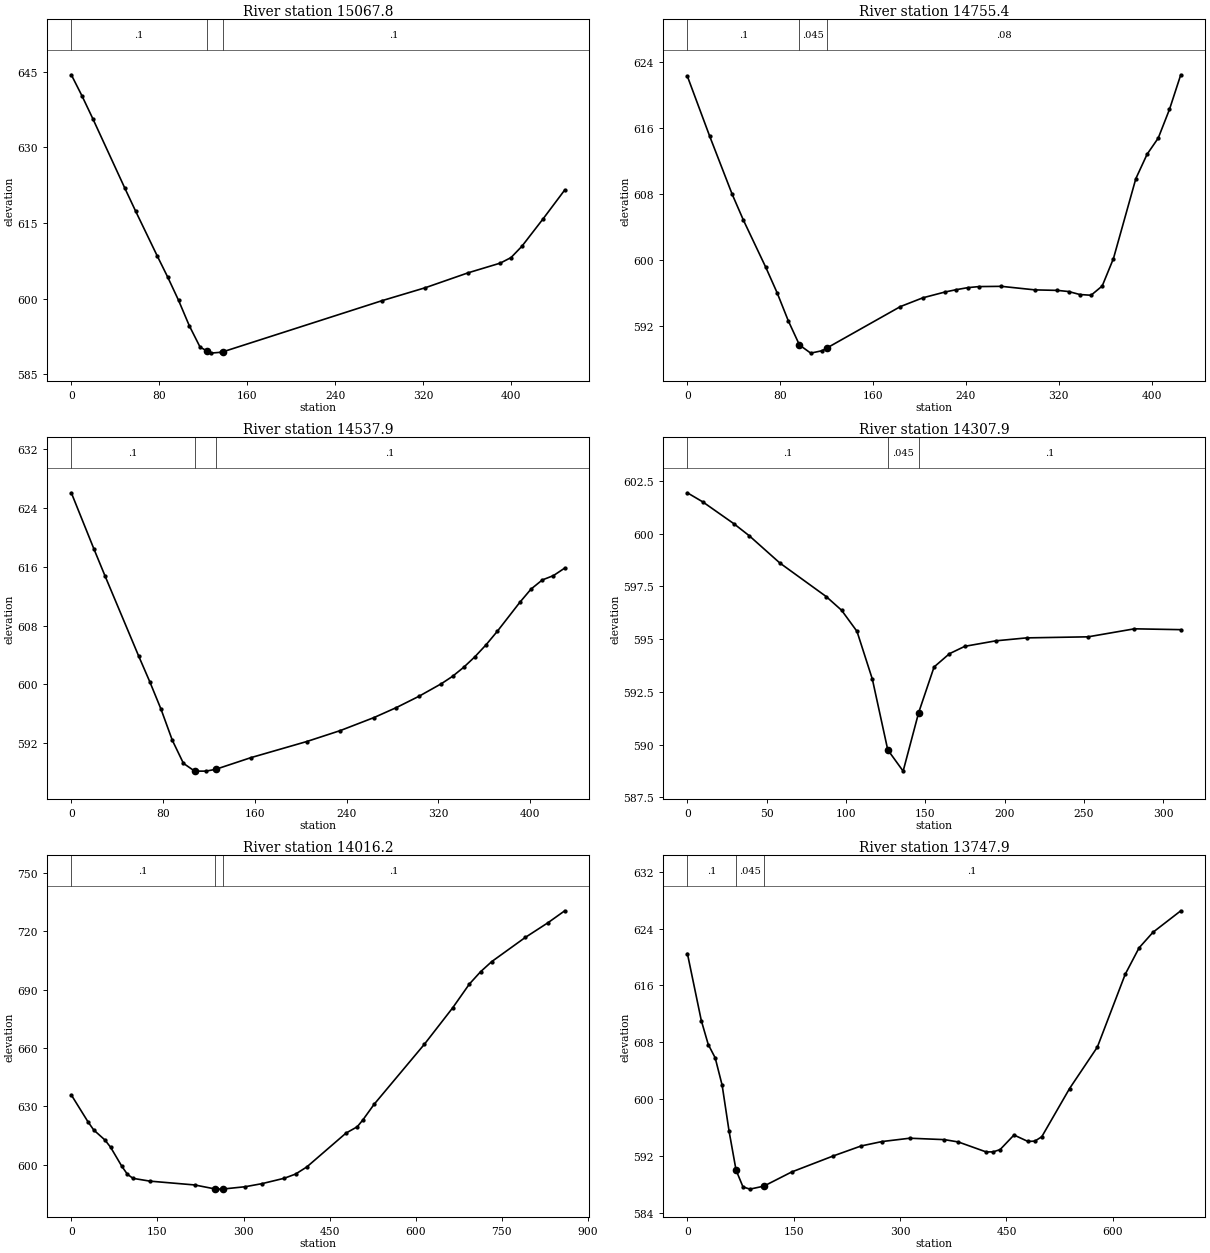
Type RM Length L Ch R = 1 ,15067.8 ,311.9,312.4,312.3
XS GIS Cut Line= 2
     1622954.079      513465.512     1623329.079       513712.04
#Sta/Elev= 22
       0  644.38     9.8  640.16    19.5   635.7    48.8  621.84    58.5  617.34
      78  608.53    87.8  604.21    97.6  599.63   107.3  594.63   117.1  590.39
     123  589.66   126.8  589.19   136.6  589.37     138  589.46   282.9  599.61
     322  602.16     361  605.12   390.2  607.04     400  608.14   409.8  610.36
   429.3  615.86   448.8  621.53
#Mann= 3 , 0 , 0
       0      .1       0     123    .045       0     138      .1       0
Bank Sta=123,138
XS Rating Curve= 0 ,0
Exp/Cntr=0.3,0.1

Type RM Length L Ch R = 1 ,14755.4 ,217.7,217.5,217.3
XS GIS Cut Line= 2
     1622783.941      513722.456     1623136.371      513960.303
#Sta/Elev= 30
       0  622.25    19.3  614.96    38.6  607.96    48.3  604.82    67.6   599.1
    77.3  596.04      87  592.62    96.6   589.7   106.3  588.72     116  589.01
   120.6  589.37   183.6  594.36   202.9  595.42   222.2  596.13   231.9  596.41
   241.6  596.65   251.2  596.78   270.6  596.81   299.6  596.38   318.9  596.32
   328.6  596.18   338.2  595.82   347.9  595.73   357.5  596.85   367.2  600.18
   386.5  609.86   396.2  612.81   405.8  614.77   415.5  618.25   425.2  622.43
#Mann= 3 , 0 , 0
       0      .1       0    96.6    .045       0   120.6     .08       0
Bank Sta=96.6,120.6
XS Rating Curve= 0 ,0
Exp/Cntr=0.3,0.1

Type RM Length L Ch R = 1 ,14537.9 ,232.5,230,226.9
XS GIS Cut Line= 2
     1622643.316      513887.387     1622999.218      514128.706
#Sta/Elev= 28
       0  626.09    19.6  618.48    29.3   614.8    58.6   603.9    68.4  600.36
    78.2  596.62      88  592.41    97.7  589.26   107.5   588.2   117.3   588.2
   125.7  588.44   156.4  590.03   205.2  592.23   234.6  593.73   263.9   595.5
   283.4  596.86     303  598.39   322.5   600.1   332.3  601.11     342  602.34
   351.8  603.78   361.6  605.42   371.4  607.26   390.9  611.18   400.7  612.99
   410.5  614.23   420.2  614.82     430  615.84
#Mann= 3 , 0 , 0
       0      .1       0   107.5    .045       0   125.7      .1       0
Bank Sta=107.5,125.7
XS Rating Curve= 0 ,0
Exp/Cntr=0.3,0.1

Type RM Length L Ch R = 1 ,14307.9 ,289.1,291.8,294.1
XS GIS Cut Line= 2
     1622515.025      514083.723     1622793.671      514221.744
#Sta/Elev= 20
       0  601.94     9.7  601.51    29.2  600.48    38.9  599.91    58.3  598.61
    87.5  597.02    97.2  596.37   106.9  595.37   116.6   593.1   126.3  589.75
     136  588.74   145.8  591.52   155.5  593.68   165.2  594.31   174.9  594.66
   194.4  594.92   213.8  595.06   252.6  595.11   281.8  595.49     311  595.45
#Mann= 3 , 0 , 0
       0      .1       0   126.3    .045       0   145.8      .1       0
Bank Sta=126.3,145.8
XS Rating Curve= 0 ,0
Exp/Cntr=0.3,0.1

Type RM Length L Ch R = 1 ,14016.2 ,265.2,268.2,270.4
XS GIS Cut Line= 2
     1622257.899      514245.026     1622999.653      514678.994
#Sta/Elev= 30
       0  635.84    29.3  621.89    39.1  617.79    58.6  612.64    68.4  608.93
    87.9  599.15    97.7  595.01   107.4  592.92   136.7  591.49   214.8  589.52
   249.9  587.49   253.9  587.37   264.9  587.45   302.7   588.6     332  590.18
   371.1  592.98   390.6  595.12   410.2  598.79   478.5  616.22     498  619.46
   507.8  622.97   527.3  630.99   615.2  662.02   664.1  680.62   693.4  692.95
   712.9  699.28   732.4  704.51     791  716.98   830.1  724.46   859.4  730.63
#Mann= 3 , 0 , 0
       0      .1       0   249.9    .045       0   264.9      .1       0
Bank Sta=249.9,264.9
XS Rating Curve= 0 ,0
Exp/Cntr=0.3,0.1

Type RM Length L Ch R = 1 ,13747.9 ,130.5,135.8,140.5
XS GIS Cut Line= 2
     1622202.199      514470.648     1622786.111      514849.133
#Sta/Elev= 30
       0  620.48    19.6  611.06    29.4  607.69    39.2  605.81      49  601.96
    58.8  595.48    68.6  590.03    78.4  587.66    88.2  587.35   107.8  587.77
     147  589.76   205.8  592.02     245  593.42   274.4  594.04   313.6  594.51
   362.6  594.31   382.2  593.98   421.4  592.58   431.2  592.59     441  592.91
   460.6  594.96   480.2  594.06     490   594.1   499.8  594.72     539   601.5
   578.2  607.33   617.4  617.55     637  621.28   656.6  623.47   695.8  626.49
#Mann= 3 , 0 , 0
       0      .1       0    68.6    .045       0   107.8      .1       0
Bank Sta=68.6,107.8
XS Rating Curve= 0 ,0
Exp/Cntr=0.3,0.1

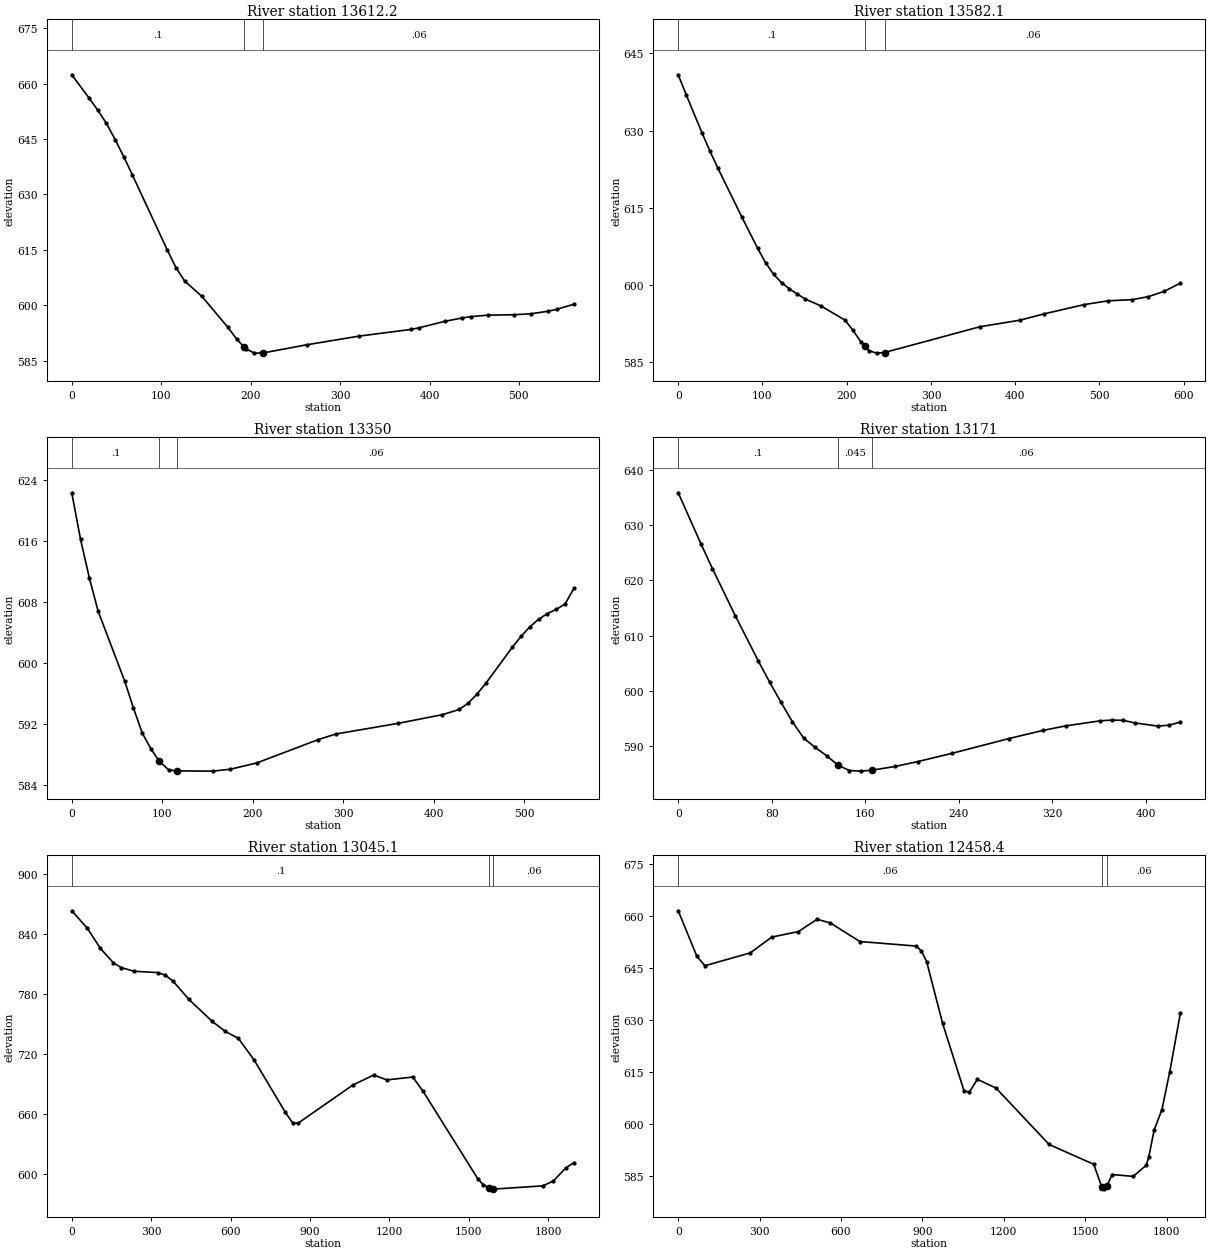
Type RM Length L Ch R = 1 ,13612.2 ,30.6,30.1,29.3
XS GIS Cut Line= 4
     1622109.968      514448.512     1622185.923      514605.847
     1622260.792      514683.972     1622481.062      514854.328
#Sta/Elev= 30
       0   662.4    19.4  656.11    29.1  652.81    38.8  649.23    48.5  644.88
    58.2  640.17    67.9  635.23   106.8  614.95   116.5  610.18   126.2  606.55
   145.6  602.36   174.7  593.96   184.6  590.76   192.8  588.64   194.4  588.23
   204.2  587.01   214.1  587.07   263.2  589.29   321.3  591.62   378.9  593.42
   388.5  593.88   417.4  595.64   436.6  596.54   446.2   596.9   465.4   597.3
   494.2  597.41   513.4  597.67   532.6  598.36   542.2  598.88   561.4  600.25
#Mann= 3 , 0 , 0
       0      .1       0   192.8    .045       0   214.1     .06       0
Bank Sta=192.8,214.1
XS Rating Curve= 0 ,0
Exp/Cntr=0.3,0.1

Type RM Length L Ch R = 1 ,13582.1 ,240.5,232.1,223.6
XS GIS Cut Line= 4
     1621965.654      514591.741     1622160.966      514624.294
     1622247.772      514710.014     1622469.126      514874.945
#Sta/Elev= 30
       0  640.81     9.4  636.96    28.3  629.51    37.7  625.98    47.1  622.68
    75.4  613.24    94.3  607.12   103.7  604.33   113.2  602.07   122.6  600.47
     132  599.26   141.4  598.23   150.9  597.27   169.7  595.92     198  593.18
   207.4  591.21   216.8  588.97   221.5  588.12   226.2  587.26   235.5  586.78
   244.9   586.9   358.1   591.9   405.7  593.18   434.2   594.4   481.8   596.2
   510.4  596.94   538.9  597.16     558  597.74     577  598.78     596  600.37
#Mann= 3 , 0 , 0
       0      .1       0   221.5    .045       0   244.9     .06       0
Bank Sta=221.5,244.9
XS Rating Curve= 0 ,0
Exp/Cntr=0.3,0.1

Type RM Length L Ch R = 1 ,13350   ,177.2,179,179.9
XS GIS Cut Line= 2
     1621937.442      514770.778     1622448.509      514986.707
#Sta/Elev= 30
       0  622.28     9.7  616.17    19.5  611.09    29.2  606.74    58.4  597.63
    68.1   594.1    77.9   590.8    87.6   588.7    96.6  587.12   107.1  585.97
   116.8  585.84   155.7  585.81   175.2  586.06   204.4  586.88   272.5  589.95
     292  590.68   360.1  592.06   408.8  593.19   428.3  593.89     438  594.71
   447.7  595.89   457.5  597.31   486.7  602.02   496.4  603.46   506.1  604.72
   515.9  605.71   525.6  606.46   535.3     607   545.1  607.71   554.8  609.75
#Mann= 3 , 0 , 0
       0      .1       0    96.6    .045       0   116.8     .06       0
Bank Sta=96.6,116.8
XS Rating Curve= 0 ,0
Exp/Cntr=0.3,0.1

Type RM Length L Ch R = 1 ,13171   ,124.7,125.9,127.3
XS GIS Cut Line= 2
     1621851.721       514918.13     1622239.742      515103.026
#Sta/Elev= 28
       0  635.81    19.5  626.56    29.3  622.09    48.8   613.6    68.4  605.47
    78.2  601.58    87.9  597.96    97.7  594.41   107.5  591.43   117.2  589.77
     127  588.27   136.8  586.55   146.5  585.59   156.3  585.48   166.1  585.66
   185.6  586.32   205.1  587.21   234.4   588.7   283.3  591.38   312.6  592.86
   332.1  593.68   361.4  594.58   371.2  594.72     381  594.66   390.8   594.2
   410.3  593.63     420  593.78   429.8  594.35
#Mann= 3 , 0 , 0
       0      .1       0   136.8    .045       0   166.1     .06       0
Bank Sta=136.8,166.1
XS Rating Curve= 0 ,0
Exp/Cntr=0.3,0.1

Type RM Length L Ch R = 1 ,13045.1 ,593,586.7,575.6
XS GIS Cut Line= 3
     1620437.659      514532.714     1621739.742       514980.63
     1622192.867      515235.839
#Sta/Elev= 30
       0  862.83      59  845.42   108.2  825.36   157.4  810.92   186.9  806.21
     236  802.52   324.6  801.22   354.1  798.64   383.6   792.4   442.6  774.47
   531.1  752.43   580.3  742.52   629.5  735.61   688.5  714.24   806.5  662.04
     836  650.71   855.7  651.12  1062.2  689.07  1140.9  699.05  1190.1  694.17
  1288.4  697.02  1327.8   682.6    1534  595.61  1553.6   589.8  1577.6  586.49
  1592.6  585.21  1779.3  588.46  1818.5  593.12  1867.6  606.59    1897  611.51
#Mann= 3 , 0 , 0
       0      .1       0  1577.6    .045       0  1592.6     .06       0
Bank Sta=1577.6,1592.6
XS Rating Curve= 0 ,0
Exp/Cntr=0.3,0.1

Type RM Length L Ch R = 1 ,12458.4 ,257.7,254.9,253.5
XS GIS Cut Line= 3
     1620198.075       515449.38     1621505.367      515517.089
     1622036.617      515621.255
#Sta/Elev= 30
       0  661.62    68.9  648.44    98.4  645.77   265.8  649.48   344.5  654.03
   442.9  655.63   511.8  659.19     561   658.1   669.3  652.76     876  651.45
   895.7  650.13   915.4  646.98   974.4  629.11  1053.1  609.69  1072.8  609.27
  1102.4  612.96  1171.2  610.44    1367  594.15  1531.4  588.42  1561.4  581.78
  1570.1  581.26  1579.7  582.11  1599.1  585.48  1676.4  584.94  1724.7  588.13
  1734.4  590.58  1753.7  598.25  1782.7  604.23  1811.7  615.22  1850.4  632.01
#Mann= 3 , 0 , 0
       0     .06       0  1561.4    .045       0  1579.7     .06       0
Bank Sta=1561.4,1579.7
XS Rating Curve= 0 ,0
Exp/Cntr=0.3,0.1

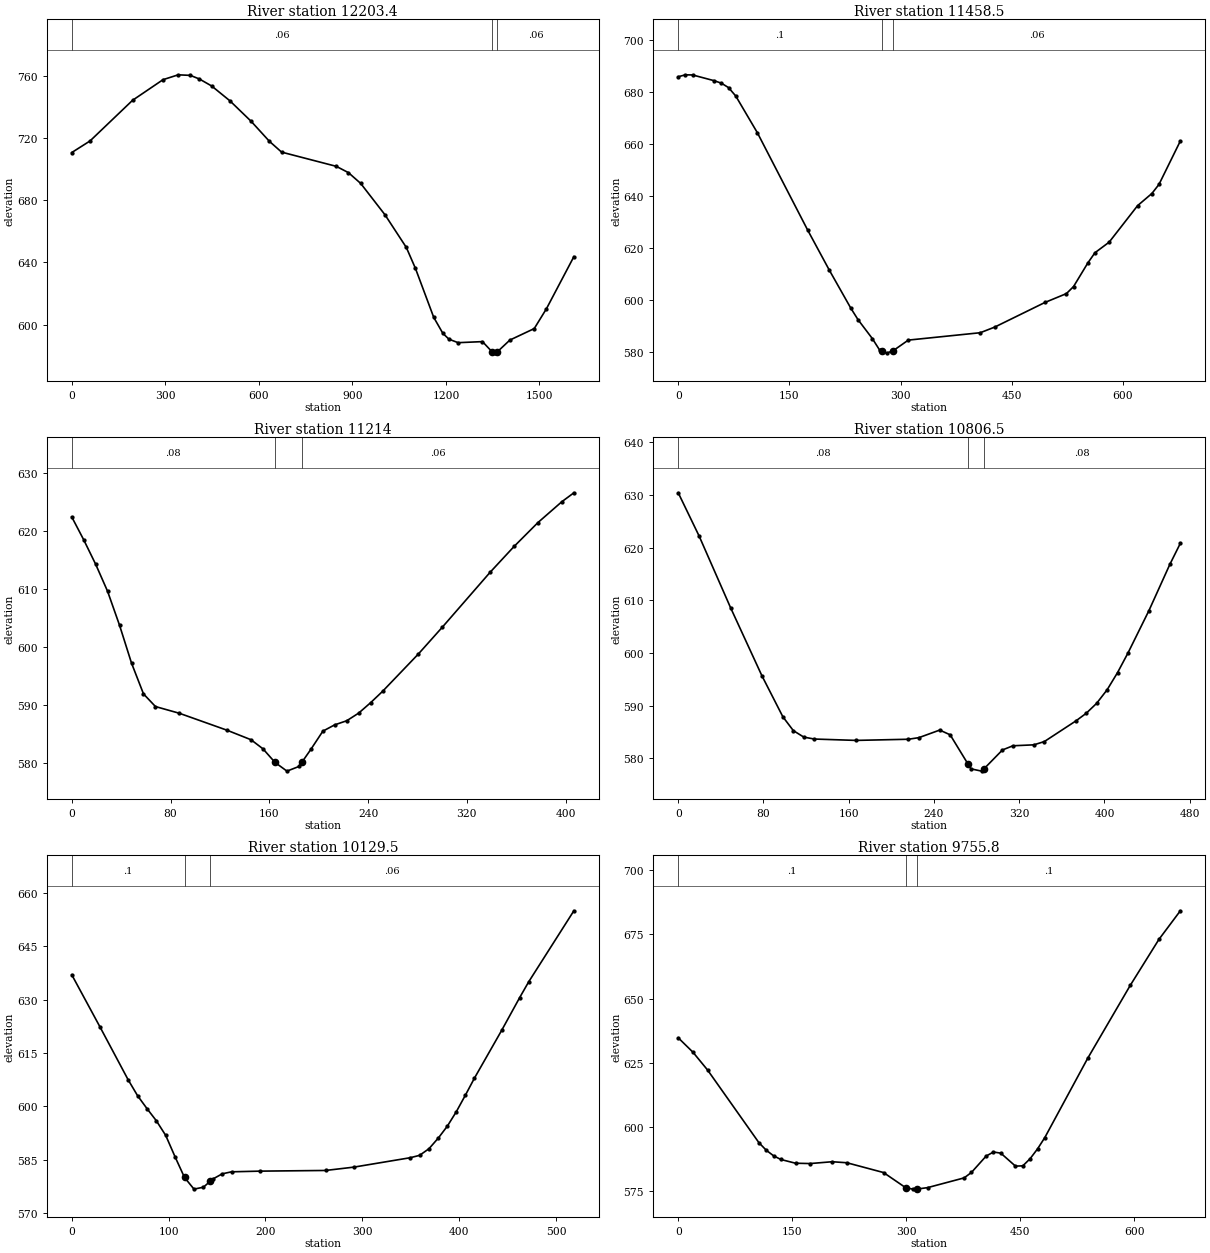
Type RM Length L Ch R = 1 ,12203.4 ,765.2,744.9,722.2
XS GIS Cut Line= 3
     1620807.016      516591.307     1621349.551      515792.696
     1621994.082      515810.057
#Sta/Elev= 30
       0  710.89    58.5  718.35     195  744.57   292.6  757.86   341.3  760.99
   380.3  760.64   409.6  758.27   448.6   753.8   507.1  744.25   575.4  730.99
   633.9  718.11   672.9  711.16   848.4  701.99   887.4  697.91   926.5     691
  1004.5  670.76  1072.9  649.72  1102.2  636.19  1160.8  604.64  1190.2   594.3
  1209.7  590.55    1239  588.31  1317.2  588.99  1348.8  582.23  1356.2  581.57
  1363.8  582.22  1405.1     590  1483.2   597.4  1522.3  610.18  1610.2  643.73
#Mann= 3 , 0 , 0
       0     .06       0  1348.8    .045       0  1363.8     .06       0
Bank Sta=1348.8,1363.8
XS Rating Curve= 0 ,0
Exp/Cntr=0.3,0.1

Type RM Length L Ch R = 1 ,11458.5 ,235.1,244.5,254
XS GIS Cut Line= 3
     1621653.371      516662.922     1621985.402      516270.127
     1622135.141      516205.023
#Sta/Elev= 30
       0  685.88     9.7  686.61    19.4  686.56    48.5  684.35    58.2   683.4
    67.9  681.69    77.6  678.47   106.8  664.33   174.7  626.87   203.8  611.52
   232.9  596.85   242.6  592.44     262  585.13   271.7  580.77   275.1  580.34
   281.4  579.55   290.1  580.49   310.5  584.56   407.6   587.4     427  589.55
   494.9  599.04   523.9  602.45   533.5  605.15   552.8  614.24   562.4  618.17
   581.6  622.25     620   636.3   639.2  640.95   648.8  644.45   677.6  661.13
#Mann= 3 , 0 , 0
       0      .1       0   275.1    .045       0   290.1     .06       0
Bank Sta=275.1,290.1
XS Rating Curve= 0 ,0
Exp/Cntr=0.3,0.1

Type RM Length L Ch R = 1 ,11214   ,399.2,407.5,415
XS GIS Cut Line= 2
     1621874.725       516636.88     1622241.478      516461.099
#Sta/Elev= 30
       0  622.39     9.7  618.44    19.4  614.22      29  609.58    38.7  603.72
    48.4   597.2    58.1  591.89    67.8  589.71    87.2  588.55   125.9  585.62
   145.2  583.99   154.9  582.42   164.6  580.09   174.3  578.58     184  579.38
   186.3  580.08   193.7  582.34   203.4  585.47     213  586.56   222.7  587.26
   232.4  588.58   242.1  590.38   251.8  592.34   280.8  598.78   300.2   603.4
   338.9  612.86   358.3  617.31   377.6  621.42     397  625.02   406.7  626.55
#Mann= 3 , 0 , 0
       0     .08       0   164.6    .045       0   186.3     .06       0
Bank Sta=164.6,186.3
XS Rating Curve= 0 ,0
Exp/Cntr=0.3,0.1

Type RM Length L Ch R = 1 ,10806.5 ,691.1,677,663.4
XS GIS Cut Line= 2
     1621840.003      516984.103     1622308.753       516936.36
#Sta/Elev= 30
       0  630.38    19.6  622.18    49.1  608.59    78.5  595.68    98.2  587.88
     108  585.26   117.8  584.03   127.6  583.66   166.9   583.4     216  583.62
   225.8  583.92   245.4  585.36   255.2  584.46   272.2  578.83   274.8     578
   284.7  577.57   287.2  578.06   304.3  581.59   314.1  582.38   333.8  582.56
   343.6  583.18     373  587.07   382.8  588.53   392.6  590.42   402.5     593
   412.3  596.27   422.1  599.99   441.7  608.01   461.4  616.81   471.2  620.79
#Mann= 3 , 0 , 0
       0     .08       0   272.2    .045       0   287.2     .08       0
Bank Sta=272.2,287.2
XS Rating Curve= 0 ,0
Exp/Cntr=0.3,0.1

Type RM Length L Ch R = 1 ,10129.5 ,362.3,373.6,382.2
XS GIS Cut Line= 3
      1622115.61      517624.294      1622419.43      517398.599
     1622540.957      517329.155
#Sta/Elev= 30
       0  637.01    29.1  622.36    58.2  607.48    67.9  603.02    77.6  599.39
    87.3  595.96      97  591.83   106.8  585.72   116.4     580   126.2  576.72
   135.9  577.26     143  578.94   145.6  579.55   155.3  581.02     165  581.59
   194.1  581.78     262  581.97   291.1   582.9   349.4  585.55   359.1  586.22
   368.8  588.08   378.5   591.1   387.8  594.44   397.1  598.52   406.5  603.19
   415.8  607.96   443.8  621.34   462.5  630.61   471.8  635.04   518.4     655
#Mann= 3 , 0 , 0
       0      .1       0   116.4    .045       0     143     .06       0
Bank Sta=116.4,143
XS Rating Curve= 0 ,0
Exp/Cntr=0.3,0.1

Type RM Length L Ch R = 1 ,9755.8  ,825.4,821.3,814.4
XS GIS Cut Line= 3
     1622191.565       517873.86     1622655.975      517743.651
     1622807.884      517650.335
#Sta/Elev= 30
       0  634.71    19.3  629.13    38.6  622.17   106.1  593.89   115.8  590.93
   125.4  588.77     135  587.33   154.3  585.87   173.6  585.74   202.6  586.45
   221.9  586.05   270.1  582.24   299.3  576.33   308.7  575.78   314.3  575.81
     328  576.36   376.2  580.16   385.8  582.28   405.2  588.68   414.8  590.23
   424.4  589.79   443.7  584.74   453.4  584.85     463  587.64   472.7  591.43
   482.3  595.85   538.6  626.66   594.9  655.22   632.4  673.02   660.6  684.17
#Mann= 3 , 0 , 0
       0      .1       0   299.3    .045       0   314.3      .1       0
Bank Sta=299.3,314.3
XS Rating Curve= 0 ,0
Exp/Cntr=0.3,0.1

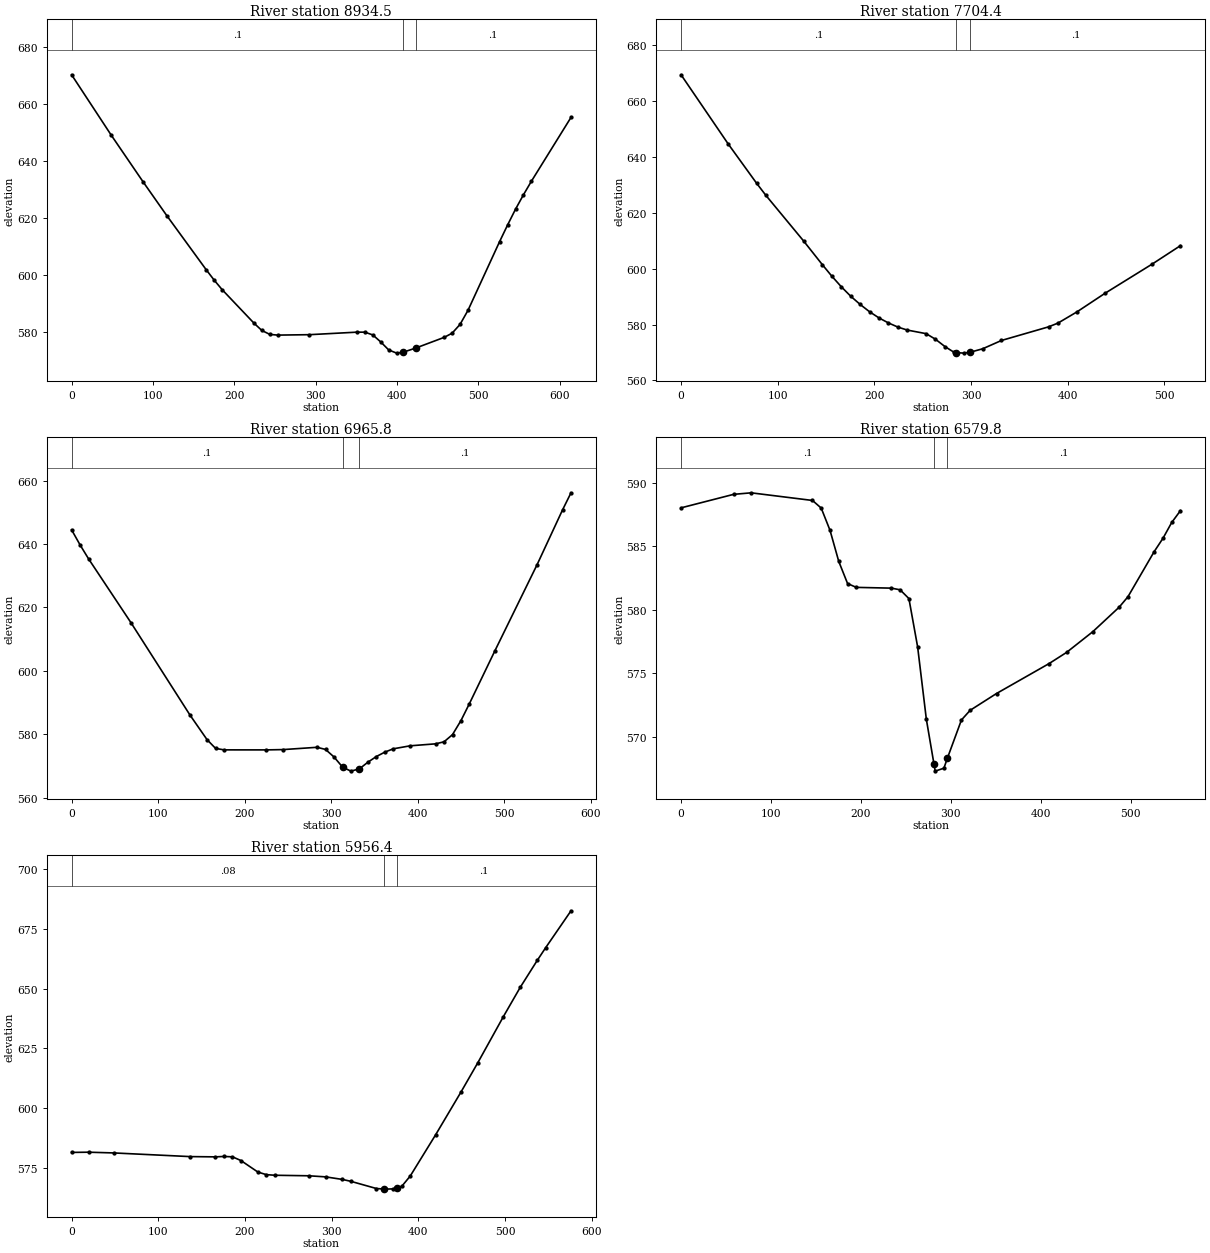
Type RM Length L Ch R = 1 ,8934.5  ,1226.7,1230.1,1233.9
XS GIS Cut Line= 2
     1622418.272      518604.762     1622987.717      518375.596
#Sta/Elev= 30
       0  670.36    48.7  649.12    87.7  632.77   116.9  620.86   165.6  601.72
   175.4  598.07   185.1  594.76   224.1  583.01   233.8  580.43   243.6  579.05
   253.3   578.8   292.3  578.95   350.8  579.84   360.5  579.83   370.2  578.86
     380  576.38   389.7  573.59   399.5  572.46   407.8  572.81   422.8  574.23
   457.9     578   467.7  579.48   477.4  582.55   487.2  587.52   526.1  611.72
   535.9  617.56   545.6  623.08   555.4  628.18   565.1  632.91   613.8  655.38
#Mann= 3 , 0 , 0
       0      .1       0   407.8    .045       0   422.8      .1       0
Bank Sta=407.8,422.8
XS Rating Curve= 0 ,0
Exp/Cntr=0.3,0.1

Type RM Length L Ch R = 1 ,7704.4  ,748.3,738.6,726.6
XS GIS Cut Line= 2
     1622810.633      519576.985     1623293.272      519392.957
#Sta/Elev= 30
       0  669.33    48.7  644.62      78   630.6    87.7  626.22   126.7  609.91
   146.2  601.39   155.9  597.32   165.7  593.53   175.4  590.16   185.2  587.21
   194.9   584.6   204.7  582.38   214.4   580.6   224.2  579.11   233.9  578.04
   253.4  576.76   263.1  574.76   272.9  572.14   282.6  570.03   284.2  569.99
   292.4  569.79   299.2  570.13   311.9  571.34   331.4  574.32   380.1  579.19
   389.8  580.53   409.3  584.51   438.6  591.22   487.3  601.65   516.5  608.23
#Mann= 3 , 0 , 0
       0      .1       0   284.2    .045       0   299.2      .1       0
Bank Sta=284.2,299.2
XS Rating Curve= 0 ,0
Exp/Cntr=0.3,0.1

Type RM Length L Ch R = 1 ,6965.8  ,386.6,386,385.2
XS GIS Cut Line= 2
     1623317.578      520229.762     1623730.772      519826.985
#Sta/Elev= 30
       0  644.44     9.8  639.68    19.6   635.3    68.5  615.22   136.9  586.02
   156.5  578.32   166.3  575.58     176  575.11   224.9   575.1   244.5   575.2
   283.6  575.92   293.4  575.24   303.2  572.86   313.2  569.64   322.7  568.41
   332.5  569.12   342.3  571.22   352.1  573.01   361.9   574.4   371.6  575.44
   391.2  576.39   420.5  577.01   430.3  577.65   440.1  579.92   449.9  584.36
   459.7  589.72     489  606.29   537.9  633.52   567.2  650.72     577  656.12
#Mann= 3 , 0 , 0
       0      .1       0   313.2    .045       0   332.5      .1       0
Bank Sta=313.2,332.5
XS Rating Curve= 0 ,0
Exp/Cntr=0.3,0.1

Type RM Length L Ch R = 1 ,6579.8  ,619.6,623.4,624.9
XS GIS Cut Line= 2
     1623577.994       520507.54     1623956.467       520101.29
#Sta/Elev= 30
       0  588.01    58.4  589.07    77.9  589.19   146.1  588.59   155.8  587.99
   165.6  586.24   175.3   583.8   185.1  582.06   194.8  581.76   233.8   581.7
   243.5  581.57   253.3  580.88     263  577.08   272.7  571.39   281.2  567.86
   282.5  567.32   292.2  567.55   296.2  568.36   311.7  571.34   321.4   572.1
   350.7  573.42   409.1  575.77   428.6  576.65   457.8  578.28     487   580.2
   496.8  581.02     526  584.57   535.8  585.62   545.5  586.86   555.2  587.79
#Mann= 3 , 0 , 0
       0      .1       0   281.2    .045       0   296.2      .1       0
Bank Sta=281.2,296.2
XS Rating Curve= 0 ,0
Exp/Cntr=0.3,0.1

Type RM Length L Ch R = 1 ,5956.4  ,5917.4,5956.4,5985.4
XS GIS Cut Line= 2
     1623935.633      520906.846     1624373.133      520531.846
#Sta/Elev= 30
       0  581.47    19.5  581.56    48.8  581.25   136.7  579.72     166  579.61
   175.8  579.78   185.6  579.62   195.3  578.08   214.9  573.26   224.6  572.18
   234.4  571.92   273.5   571.7     293  571.25   312.5  570.17   322.3  569.37
   351.6  566.38   360.6  566.14   361.4  566.12   371.1  566.22   375.6  566.71
   380.9  567.28   390.7  571.59     420  588.84   449.3  606.74   468.8  619.04
   498.1   638.2   517.6  650.47   537.2  661.72   546.9  667.03   576.2  682.48
#Mann= 3 , 0 , 0
       0     .08       0   360.6    .045       0   375.6      .1       0
Bank Sta=360.6,375.6
XS Rating Curve= 0 ,0
Exp/Cntr=0.3,0.1

Chan Stop Cuts=-1
Use User Specified Reach Order=0
Composite Channel Slope=5